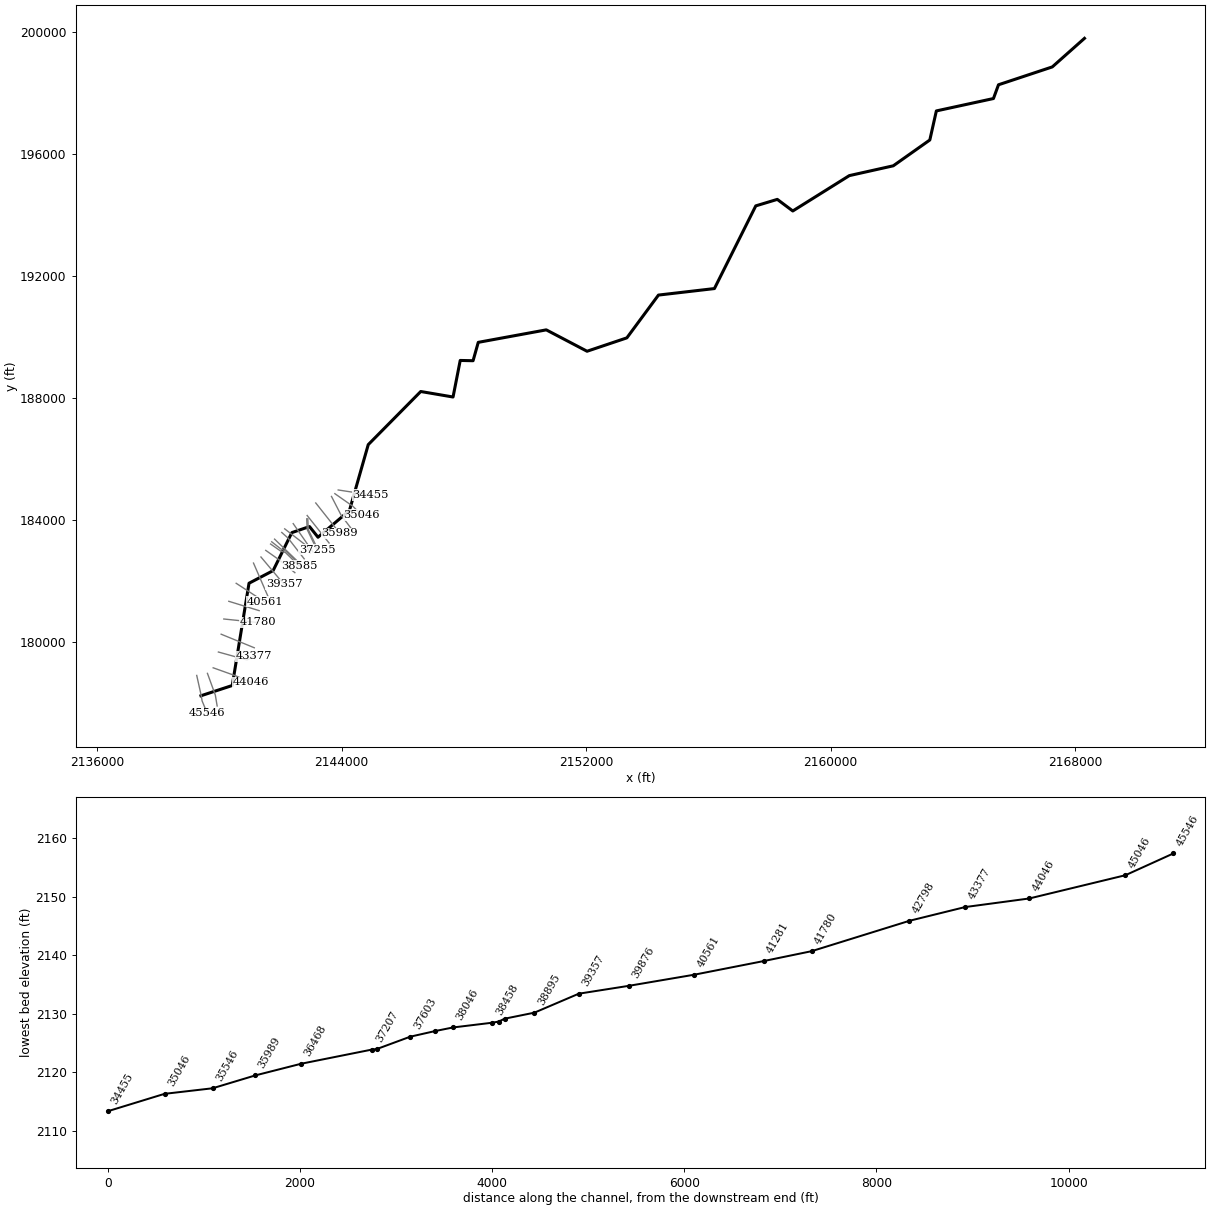
--- POTTSCK.prj (project) ---

Proj Title=POTTSCK
Current Plan=p01
Default Exp/Contr=0,0
English Units
Geom File=g01
Flow File=f01
Plan File=p01
Background Map Layer=Inundation Boundary (01pct Value_0)
BEGIN DESCRIPTION:
Stream Name: Potts Creek
Flood Zone: Approximate
Monroe County, West Virginia
HEC-RAS Version: 5.0.7
Vertical Datum: NAVD88
Projection: NAD 1983 StatePlane West Virginia S FIPS 4702 (US Feet)
LiDAR: 2016, 1-meter
Land Use: 2016 NLCD
Hydrologic Method:
Regression
Model Notes:
Extended beyond county boundary. Effective information not available beyond county boundary. Used Normal Depth.
END DESCRIPTION:
DSS File=dss
DSS Export Rating Curves= 0
DSS Export Rating Curve Sorted= 0
DSS Export Volume Flow Curves= 0
DXF OffsetX= 0
DXF OffsetY= 0
DXF ScaleX= 0
DXF ScaleY= 0

--- POTTSCK.p01 (plan) ---

Plan Title=Floodplain
Program Version=5.07
Short Identifier=Floodplain
Geom File=g01
Flow File=f01
Subcritical Flow
K Sum by GR= 0
Std Step Tol= 0.01
Critical Tol= 0.01
Num of Std Step Trials= 20
Max Error Tol= 0.3
Flow Tol Ratio= 0.001
Split Flow NTrial= 30
Split Flow Tol= 0.02
Split Flow Ratio= 0.02
Log Output Level= 0
Friction Slope Method= 1
Unsteady Friction Slope Method= 2
Unsteady Bridges Friction Slope Method= 1
Parabolic Critical Depth
Global Vel Dist= 0 , 0 , 0
Global Log Level= 0
CheckData=True
Encroach Param=-1 ,0,0, 0
Computation Interval=0.1SEC
Output Interval=1MIN
Instantaneous Interval=Max Profile
Mapping Interval=1HOUR
Computation Time Step Use Courant=        0
Computation Time Step Use Time Series=    0
Computation Time Step Count To Double=0
Computation Time Step Max Doubling=0
Computation Time Step Max Halving=0
Computation Time Step Residence Courant=0
Run HTab= 0
Run UNet= 0
Run Sediment= 0
Run PostProcess= 0
Run WQNet= 0
Run RASMapper=-1
UNET Theta= 0
UNET Theta Warmup= 0
UNET ZTol= 0
UNET ZSATol= 0
UNET MxIter= 0
UNET Max Iter WO Improvement= 0
UNET MaxInSteps= 0
UNET DtIC= 0
UNET DtMin= 0
UNET MaxCRTS= 0
UNET WFStab= 0
UNET SFStab= 0
UNET WFX= 1
UNET SFX= 1
UNET 1D Methodology=Finite Difference
UNET DSS MLevel= 1
UNET Pardiso=0
UNET DZMax Abort= 0
UNET Use Existing IB Tables= 0
UNET Froude Reduction=False
UNET Froude Limit= 0
UNET Froude Power= 0
UNET D1 Cores= 0
UNET D2 Coriolis=0
UNET D2 Cores= 0
UNET D2 Theta= 1
UNET D2 Theta Warmup= 1
UNET D2 Z Tol= 0.01
UNET D2 Volume Tol= 0.01
UNET D2 Max Iterations= 20
UNET D2 Equation= 0
UNET D2 RampUpFraction=0.1
UNET D2 TimeSlices= 1
UNET D2 BCVolumeCheck=0
UNET D1D2 MaxIter= 0
UNET D1D2 ZTol=0.01
UNET D1D2 QTol=0.1
UNET D1D2 MinQTol=1
Write IC File= 0
Write IC File at Fixed DateTime=0
Write IC File at Sim End=0
Echo Input=False
Echo Parameters=False
Echo Output=False
Write Detailed= 0
HDF Write Warmup=0
HDF Write Time Slices=0
HDF Flush=0
HDF Face Node Velocities=0
HDF Compression= 1
HDF Chunk Size= 1
HDF Spatial Parts= 1
HDF Use Max Rows=0
HDF Fixed Rows= 1
Calibration Method= 0
Calibration Iterations= 20
Calibration Max Change=0.05
Calibration Tolerance=0.2
Calibration Maximum=1.5
Calibration Minimum=0.5
Calibration Optimization Method= 1
WQ AD Non Conservative
WQ ULTIMATE=-1
WQ Max Comp Step=1HOUR
WQ Output Interval=15MIN
WQ Output Selected Increments= 0
WQ Output face flow=0
WQ Output face velocity=0
WQ Output face area=0
WQ Output face dispersion=0
WQ Output cell volume=0
WQ Output cell surface area=0
WQ Output cell continuity=0
WQ Output cumulative cell continuity=0
WQ Output face conc=0
WQ Output face dconc_dx=0
WQ Output face courant=0
WQ Output face peclet=0
WQ Output face adv mass=0
WQ Output face disp mass=0
WQ Output cell mass=0
WQ Output cell source sink temp=0
WQ Output nsm pathways=0
WQ Output nsm derived pathways=0
WQ Output MaxMinRange=-1
WQ Daily Max Min Mean=-1
WQ Daily Range=0
WQ Daily Time=0
WQ Create Restart=0
WQ Fixed Restart=0
WQ System Summary=0
WQ Write To DSS=0
WQ Use Fixed Temperature=0
Sorting and Armoring Iterations= 10
XS Update Threshold= 0.02
Bed Roughness Predictor= 0
Hydraulics Update Threshold= 0.02
Energy Slope Method= 1
Volume Change Method= 1
Sediment Retention Method= 0
XS Weighting Method= 0
Number of US Weighted Cross Sections= 1
Number of DS Weighted Cross Sections= 1
Upstream XS Weight=0
Main XS Weight=1
Downstream XS Weight=0
Number of DS XS's Weighted with US Boundary= 1
Upstream Boundary Weight= 1
Weight of XSs Associated with US Boundary= 0
Number of US XS's Weighted with DS Boundary= 1
Downstream Boundary Weight= 0.5
Weight of XSs Associated with DS Boundary= 0.5
Percentile Method= 0
Sediment Output Level= 3
Mass or Volume Output= 0
Output Increment Type= 1
Profile and TS Output Increment= 1
XS Output Flag= 0
XS Output Increment= 10
Write Gradation File= 0
Read Gradation Hotstart= 0
Write HDF5 File= 1
Write Binary Output= 1
Write DSS Sediment File= 0
SV Curve= 0
Specific Gage Flag= 0

--- POTTSCK.f01 (steady flow) ---

Flow Title=Flow
Program Version=5.07
Number of Profiles= 6
Profile Names=01pct,10pct,04pct,02pct,0_2pct,01plus
River Rch & RM=POTTSCK,Main            ,45546
    3700    2100    2700    3190    5000    5480
River Rch & RM=POTTSCK,Main            ,44046
    4110    2350    3010    3540    5540    6080
River Rch & RM=POTTSCK,Main            ,38895
    4550    2610    3330    3920    6120    6730
River Rch & RM=POTTSCK,Main            ,33046
    4930    2830    3620    4260    6620    7300
River Rch & RM=POTTSCK,Main            ,26140
    5480    3160    4030    4730    7330    8100
River Rch & RM=POTTSCK,Main            ,16631
    6040    3500    4450    5220    8070    8940
River Rch & RM=POTTSCK,Main            ,13098
    6100    3530    4490    5270    8140    9010
Boundary for River Rch & Prof#=POTTSCK,Main            , 1
Up Type= 0
Dn Type= 3
Dn Slope=0.00116
Boundary for River Rch & Prof#=POTTSCK,Main            , 2
Up Type= 0
Dn Type= 3
Dn Slope=0.00116
Boundary for River Rch & Prof#=POTTSCK,Main            , 3
Up Type= 0
Dn Type= 3
Dn Slope=0.00116
Boundary for River Rch & Prof#=POTTSCK,Main            , 4
Up Type= 0
Dn Type= 3
Dn Slope=0.00116
Boundary for River Rch & Prof#=POTTSCK,Main            , 5
Up Type= 0
Dn Type= 3
Dn Slope=0.00116
Boundary for River Rch & Prof#=POTTSCK,Main            , 6
Up Type= 0
Dn Type= 3
Dn Slope=0.00116
DSS Import GetInterval= 0
DSS Import GetPeak= 0
DSS Import FillOption= 0

--- POTTSCK.g01 (geometry) ---

Geom Title=Geometry
Program Version=5.07

River Reach=POTTSCK         ,Main
Reach XY= 30
     2139400.474178253.9570000132140424.99700001      178590.025
     2140973.477 181937.898000022141761.23800002182350.224999992
2142374.30200001183594.7990000172142951.55900002183793.367000007
2143230.42200001183443.9740000212144259.06799999184318.541000011
2144874.30200001186475.6590000192146591.96700001 188215.02500002
2147648.82500001188034.903000016     2147883.382189231.865000023
     2148303.955189222.751000002      2148473.66189824.313000003
2150698.92000001190233.1669999952152033.55500001189532.862999995
2153335.63900001 189971.231000022154369.71000001      191372.056
     2156200.584191585.0910000032157553.66500001194292.338999995
2158257.87600002194505.0130000112158764.60300002194125.239000014
     2160614.646195283.0079999942162052.36299999195604.189000025
      2163248.24196449.588000005     2163461.999197401.193999993
2165329.99200001197806.4429999942165494.92200002198256.964000012
     2167255.339198842.0330000052168308.28566963199777.461400742

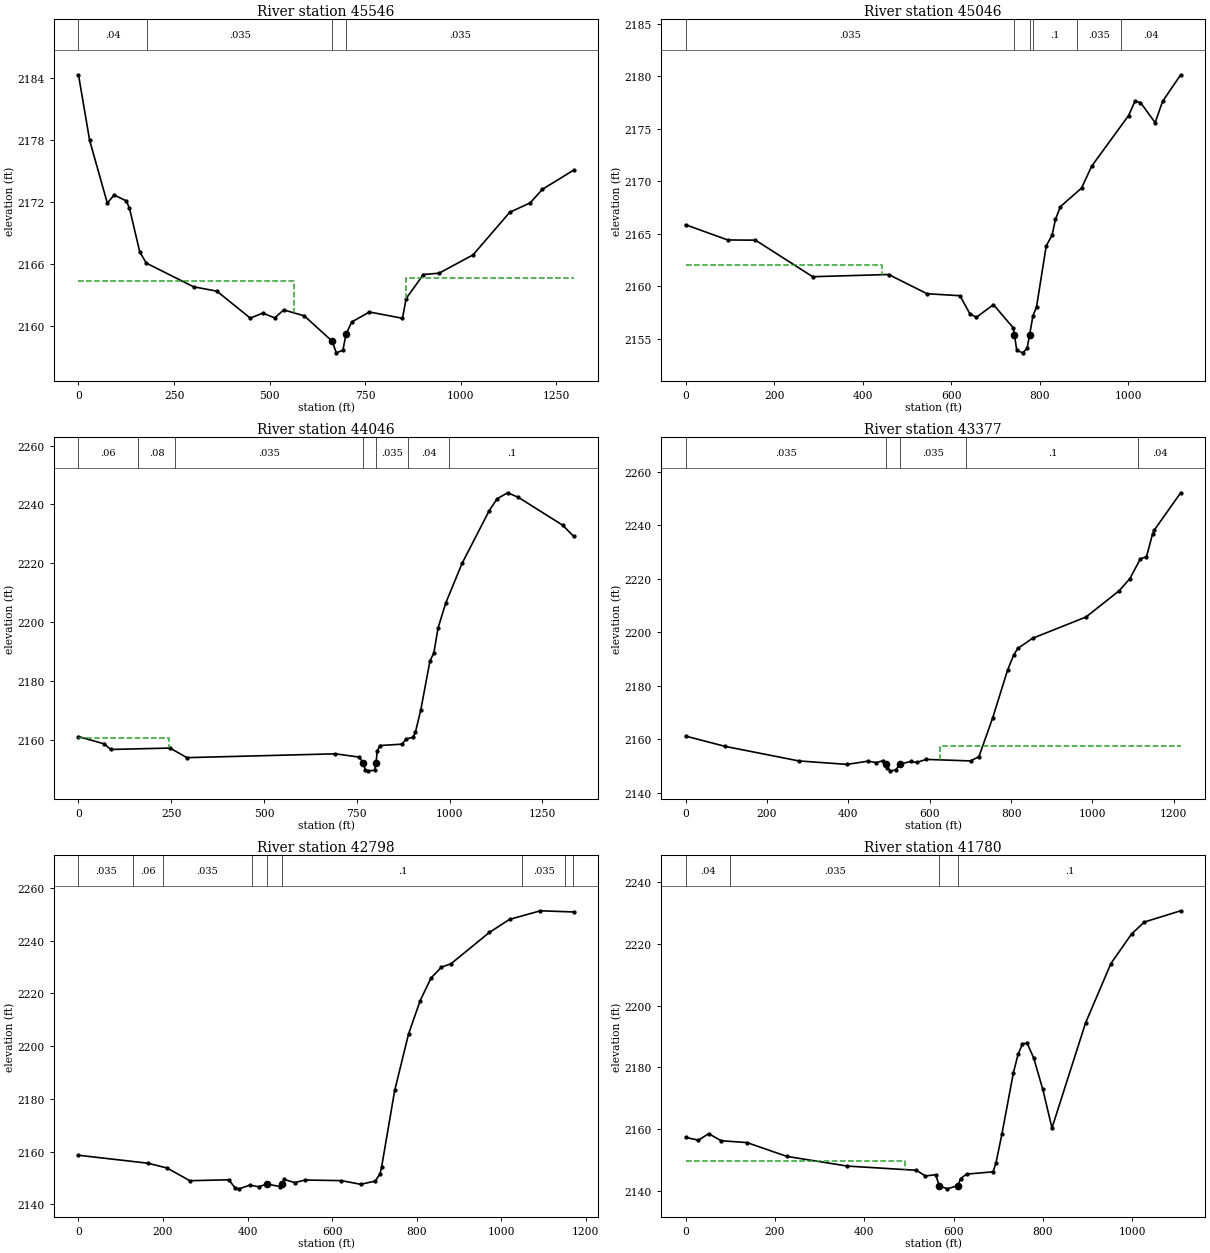
Type RM Length L Ch R = 1 ,45546   ,500,500,500
XS GIS Cut Line= 4
     2139262.552      178919.465     2139410.235       178256.13
2139438.25767566178084.1498838232139608.86875611177677.259070725
#Sta/Elev= 30
       0 2184.34  29.1942177.977  75.4212171.898  93.0562172.682 124.9052172.122
  133.392171.402  160.282167.165 177.3732166.083 300.848 2163.79 361.9492163.361
 449.339 2160.75 482.2892161.235 513.2012160.774  536.732161.543 590.5082160.972
   663.22158.522 674.5372157.384 691.6842157.645   699.62159.162 714.4822160.375
 761.0192161.343 847.4462160.734  857.022162.647 902.1472164.977 943.0522165.103
1031.9922166.8821128.0462171.012 1181.412171.9191213.4282173.2371295.0362175.093
#Mann= 4 ,-1 , 0
       0     .04       0     180    .035       0   663.2    .045       0
   699.6    .035       0
#XS Ineff= 2 , 0
          564.71 2164.38  856.97         2164.63
Permanent Ineff=
       F       F
Bank Sta=663.2,699.6
XS Rating Curve= 0 ,0
Exp/Cntr=0.3,0.1

Type RM Length L Ch R = 1 ,45046   ,984,1000,1024.8
XS GIS Cut Line= 3
     2139613.074      178986.962      2139870.79      178277.906
      2139930.93      177918.814
#Sta/Elev= 30
       0 2165.86    95.2 2164.41     158 2164.39   287.2 2160.91   458.7 2161.12
   545.5 2159.29     620  2159.1   642.6 2157.36   657.2 2157.05   695.6 2158.25
   740.3 2156.04  742.992155.354   748.3 2153.91   761.6 2153.66   771.5 2154.08
   777.4  2155.4   784.8 2157.19   792.9 2158.03   814.8 2163.85   828.1 2164.87
   835.6 2166.37     847 2167.59   894.6 2169.35   917.4 2171.43  1000.9 2176.26
  1015.1 2177.61  1027.7  2177.5  1060.9 2175.58  1077.6  2177.6  1118.5 2180.14
#Mann= 6 ,-1 , 0
       0    .035       0  742.99    .045       0   777.4    .035       0
  784.44      .1       0  884.44    .035       0  984.44     .04       0
#XS Ineff= 2 , 0
          443.34 2162.06
Permanent Ineff=
       F       F
Bank Sta=742.99,777.4
XS Rating Curve= 0 ,0
Exp/Cntr=0.3,0.1

Type RM Length L Ch R = 1 ,44046   ,666.4,668.9,669.8
XS GIS Cut Line= 3
      2139800.28      179169.585     2140533.672      178907.463
     2141046.459      178694.844
#Sta/Elev= 30
       0 2161.31    69.2 2158.83    86.6 2156.94   246.8 2157.41     292 2154.16
   692.4 2155.46   755.5 2154.36   767.62152.428   772.9 2149.81   779.7 2149.69
   797.7 2149.87   801.72152.429   804.8 2156.38   811.9 2158.27   871.6 2158.73
   882.9  2160.5   900.7 2161.05   907.6 2162.72     922 2170.24   946.9 2186.94
   957.5  2189.7   968.6 2198.07   989.5 2206.61  1033.3    2220  1106.7 2237.95
    1128 2241.96  1156.3 2243.97  1184.8 2242.45  1304.4 2232.98  1333.9 2229.23
#Mann= 7 ,-1 , 0
       0     .06       0     160     .08       0     260    .035       0
   767.6    .045       0   801.7    .035       0  888.83     .04       0
  998.83      .1       0
#XS Ineff= 2 , 0
          242.72 2160.88
Permanent Ineff=
       F       F
Bank Sta=767.6,801.7
XS Rating Curve= 0 ,0
Exp/Cntr=0.3,0.1

Type RM Length L Ch R = 1 ,43377   ,577.1,578.2,568.3
XS GIS Cut Line= 3
      2139971.19      179685.839      2140908.69      179425.422
      2141123.96      179539.928
#Sta/Elev= 30
       0 2161.21    97.9 2157.34   278.4 2151.92   397.1 2150.63   448.6 2151.84
   469.1 2151.28   486.1 2152.07  492.982150.826   496.3 2149.37   503.7 2148.22
   516.2 2148.51   527.42150.779   554.2 2151.72   567.8 2151.35   591.7  2152.5
   700.6 2151.92     721 2153.51   755.1 2168.15   791.5 2185.89   806.2 2191.39
   816.4 2193.96   852.8 2197.75   984.2  2205.7  1065.9 2215.54  1092.1 2220.08
  1117.9 2227.46  1132.8 2228.21  1147.7 2236.72  1151.4 2238.05  1216.8 2252.12
#Mann= 5 ,-1 , 0
       0    .035       0  492.98    .045       0   527.4    .035       0
     690      .1       0    1113     .04       0
#XS Ineff= 2 , 0
                          625.59         2157.43
Permanent Ineff=
       F       F
Bank Sta=492.98,527.4
XS Rating Curve= 0 ,0
Exp/Cntr=0.3,0.1

Type RM Length L Ch R = 1 ,42798   ,993.5,1018.2,995.2
XS GIS Cut Line= 2
     2140061.468      180269.172     2141145.246       179825.52
#Sta/Elev= 30
       0 2158.62   164.3  2155.6   209.6 2153.78   263.2 2148.97   355.4 2149.31
   370.6 2146.24   380.2 2145.88     405 2147.29   426.3 2146.68   446.12147.707
   475.9 2146.76   482.22147.718   486.5 2149.44   511.3 2148.25   536.2 2149.23
   622.1 2148.99   667.4  2147.6   702.1 2148.83   713.4 2151.66     717 2154.19
   747.9 2183.19   780.6 2204.56   808.2 2217.27   833.9 2225.87   858.5 2229.96
   881.2 2231.27   971.7 2243.12  1019.5 2248.08  1092.7 2251.35  1171.1  2250.9
#Mann= 9 ,-1 , 0
       0    .035       0     130     .06       0     200    .035       0
     410      .1       0   446.1    .045       0   482.2      .1       0
    1050    .035       0    1150      .1       0    1170    .035       0
Bank Sta=446.1,482.2
XS Rating Curve= 0 ,0
Exp/Cntr=0.3,0.1

Type RM Length L Ch R = 1 ,41780   ,503.2,499.4,494
XS GIS Cut Line= 2
     2140148.431      180767.235     2141251.074      180653.065
#Sta/Elev= 30
       0 2157.34    28.8 2156.44    51.9 2158.54    79.6 2156.26   137.6 2155.66
   226.7 2151.19   361.9 2148.06     517 2146.69   536.9 2144.84   559.8 2145.27
  568.452141.621   586.2 2140.69     6102141.763   615.9 2144.02   629.1 2145.45
   688.5  2146.2   695.1 2149.13   708.3 2158.42   734.1 2178.32   744.5 2184.22
   754.4 2187.63   764.7 2187.85   779.5 2183.03   799.9 2172.85   820.4 2160.39
   895.5 2194.34   952.3 2213.59   998.5 2223.15    1027 2227.02  1108.5 2230.67
#Mann= 4 ,-1 , 0
       0     .04       0     100    .035       0  568.45    .045       0
     610      .1       0
#XS Ineff= 2 , 0
           490.4 2149.63
Permanent Ineff=
       F       F
Bank Sta=568.45,610
XS Rating Curve= 0 ,0
Exp/Cntr=0.3,0.1

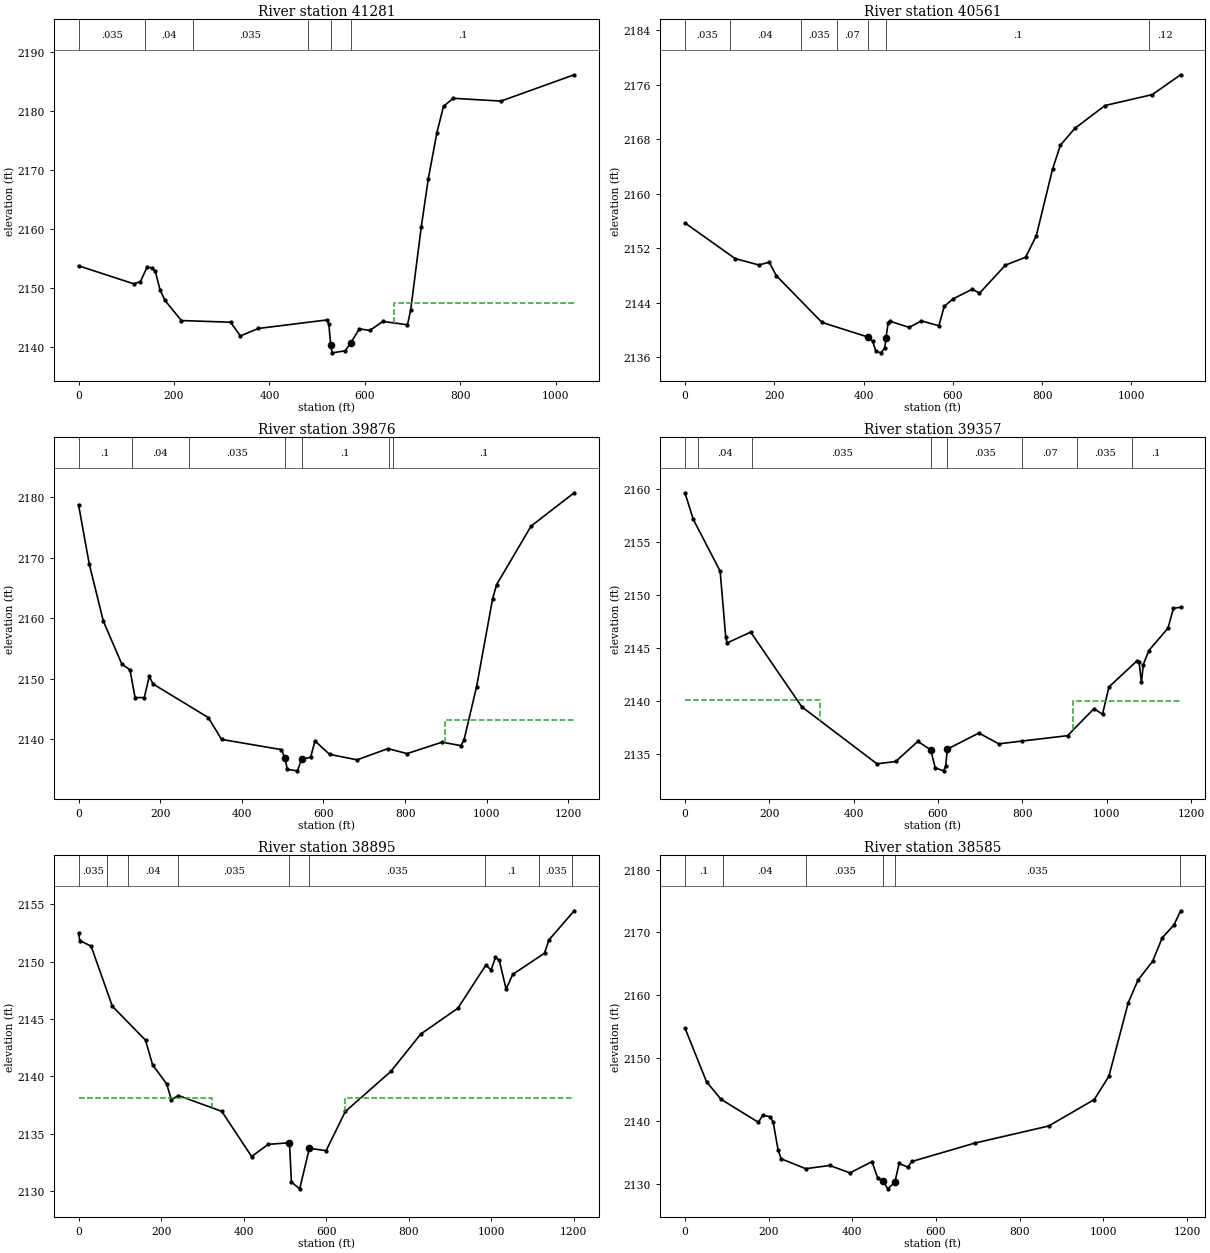
Type RM Length L Ch R = 1 ,41281   ,726.9,719.8,712.5
XS GIS Cut Line= 2
     2140312.357      181346.335     2141304.788      181040.739
#Sta/Elev= 30
       0 2153.75   115.9 2150.69   129.7 2151.07   143.4 2153.47   153.7 2153.41
   160.6 2152.87   170.8 2149.68   181.1 2147.89   215.5 2144.47   318.5 2144.19
   339.1 2141.87   376.8 2143.13   520.1 2144.57   524.4 2143.91  528.222140.377
   531.3    2139   558.8 2139.34     5702140.641   588.4 2143.07   610.3 2142.79
   637.7 2144.32   689.2 2143.75     696  2146.3   717.9 2160.24   732.7 2168.43
   750.8 2176.29   764.7 2180.77   785.2 2182.13   884.9 2181.65  1038.4 2186.11
#Mann= 6 ,-1 , 0
       0    .035       0     140     .04       0     240    .035       0
     480      .1       0  528.22    .045       0     570      .1       0
#XS Ineff= 2 , 0
                           661.3         2147.43
Permanent Ineff=
       F       F
Bank Sta=528.22,570
XS Rating Curve= 0 ,0
Exp/Cntr=0.3,0.1

Type RM Length L Ch R = 1 ,40561   ,694.6,684.9,665.4
XS GIS Cut Line= 2
     2140553.606      181935.828      2141483.62      181329.151
#Sta/Elev= 30
       0 2155.73   112.2 2150.51   165.4 2149.57   188.9 2149.97   204.6    2148
   306.7 2141.15   409.42139.008   420.1 2138.41   427.9 2136.89   439.3 2136.68
   447.5 2137.41  450.412138.923   455.3 2141.12   458.3 2141.34   502.3 2140.41
   529.7 2141.37   568.9 2140.65   580.7 2143.49   600.9 2144.61     644 2146.02
   659.8 2145.42   717.8 2149.54   763.1  2150.7   787.1 2153.86   823.5 2163.64
   841.1 2167.13   873.2 2169.59     941 2172.95  1046.8 2174.55  1110.4 2177.46
#Mann= 7 ,-1 , 0
       0    .035       0     100     .04       0     260    .035       0
     340     .07       0   409.4    .045       0  450.41      .1       0
    1040     .12       0
Bank Sta=409.4,450.41
XS Rating Curve= 0 ,0
Exp/Cntr=0.3,0.1

Type RM Length L Ch R = 1 ,39876   ,511.3,519.4,524.2
XS GIS Cut Line= 2
     2141120.162      182598.243     2141603.134       181484.45
#Sta/Elev= 30
       0 2178.81    26.3 2168.99    60.7 2159.55   106.1 2152.43     126 2151.48
   138.5  2146.9     161 2146.88   173.4  2150.4   182.3 2149.15   317.9 2143.58
   350.4 2139.97     497 2138.28  505.632136.877   511.3 2135.02   536.3 2134.77
   546.52136.699   568.5 2137.02   579.2 2139.71   614.9  2137.5   682.3 2136.59
     758 2138.45   804.6 2137.62   890.4 2139.51   936.4 2138.94     944 2139.82
   975.1 2148.72    1014 2163.15    1024 2165.57  1108.5 2175.26    1214 2180.77
#Mann= 7 ,-1 , 0
       0      .1       0     130     .04       0     270    .035       0
  505.63    .045       0   546.5      .1       0     760    .035       0
     770      .1       0
#XS Ineff= 2 , 0
                          896.56         2143.15
Permanent Ineff=
       F       F
Bank Sta=505.63,546.5
XS Rating Curve= 0 ,0
Exp/Cntr=0.3,0.1

Type RM Length L Ch R = 1 ,39357   ,453.3,462.1,456.9
XS GIS Cut Line= 2
     2141363.551       182796.95     2142120.495      181897.645
#Sta/Elev= 30
       0 2159.61    19.5 2157.12    83.4 2152.23    96.7    2146    99.9 2145.47
   155.8 2146.49     277 2139.46   455.3 2134.09   499.8 2134.31   552.1  2136.2
   582.82135.411   593.5 2133.71   613.2 2133.43   618.3 2133.86   622.12135.471
     697 2136.99   744.2 2135.97     800 2136.24   907.2 2136.74   969.9 2139.28
   990.2 2138.76  1005.5 2141.33  1071.8 2143.78  1076.9 2143.67  1082.5 2141.76
    1087 2143.44  1100.1 2144.76  1145.4 2146.86  1158.4 2148.73  1175.5 2148.83
#Mann= 8 ,-1 , 0
       0    .035       0      30     .04       0     160    .035       0
   582.8    .045       0   622.1    .035       0     800     .07       0
     930    .035       0    1060      .1       0
#XS Ineff= 2 , 0
          320.74 2140.08  921.36         2140.03
Permanent Ineff=
       F       F
Bank Sta=582.8,622.1
XS Rating Curve= 0 ,0
Exp/Cntr=0.3,0.1

Type RM Length L Ch R = 1 ,38895   ,303.3,310.1,316.6
XS GIS Cut Line= 3
     2141520.896      183013.556     2141974.944      182692.836
     2142473.432      182283.738
#Sta/Elev= 30
       0 2152.48     3.2 2151.85    30.5 2151.36      82 2146.12   162.3 2143.16
   179.5 2141.01   213.6 2139.34     225 2137.96   242.1 2138.33   347.1 2136.95
   419.4 2133.01   459.5 2134.07  511.092134.211   515.8 2130.78   535.9 2130.19
   559.22133.728   599.8 2133.52   646.4 2136.94   756.6 2140.43     829 2143.69
   919.1 2145.95   986.7  2149.7   999.7 2149.29  1010.1 2150.38  1019.4 2150.13
  1035.9 2147.62    1052  2148.9    1129 2150.75  1139.3 2151.89  1200.8 2154.45
#Mann= 9 ,-1 , 0
       0    .035       0      70      .1       0     120     .04       0
     240    .035       0  511.09    .045       0   559.2    .035       0
   985.9      .1       0  1115.9    .035       0  1195.9      .1       0
#XS Ineff= 2 , 0
          323.63 2138.11  645.82         2138.15
Permanent Ineff=
       F       F
Bank Sta=511.09,559.2
XS Rating Curve= 0 ,0
Exp/Cntr=0.5,0.3

Type RM Length L Ch R = 1 ,38585   ,67.3,61.7,57.8
XS GIS Cut Line= 4
2141678.27917669183221.6103426592142013.07269696182987.998864072
2142161.86981707182946.3356704392142606.77320623182511.848079692
#Sta/Elev= 30
       0 2154.77    51.5 2146.22    85.8 2143.44   175.4 2139.76   185.8 2140.87
   203.6 2140.65   210.7  2139.8   222.5 2135.37   229.8 2133.95   288.5 2132.37
   345.8 2132.88   394.5  2131.7     447  2133.5   460.7 2130.85   474.3 2130.36
   484.5 2129.16   501.6  2130.2   511.8 2133.22   532.2 2132.62   542.4 2133.52
   692.9 2136.45   869.3 2139.17   978.3 2143.39  1013.1 2147.09  1059.5 2158.82
  1082.7  2162.4  1117.8 2165.42  1140.7 2169.16  1168.6 2171.19  1184.6 2173.45
#Mann= 6 ,-1 , 0
       0      .1       0      90     .04       0     290    .035       0
   474.3    .045       0   501.6    .035       0 1182.76      .1       0
#XS Ineff= 2 , 0
          462.46 2130.67  508.88         2130.67
Permanent Ineff=
       F       F
Bank Sta=474.3,501.6
XS Rating Curve= 0 ,0
Exp/Cntr(USF)=0,0
Exp/Cntr=0.5,0.3

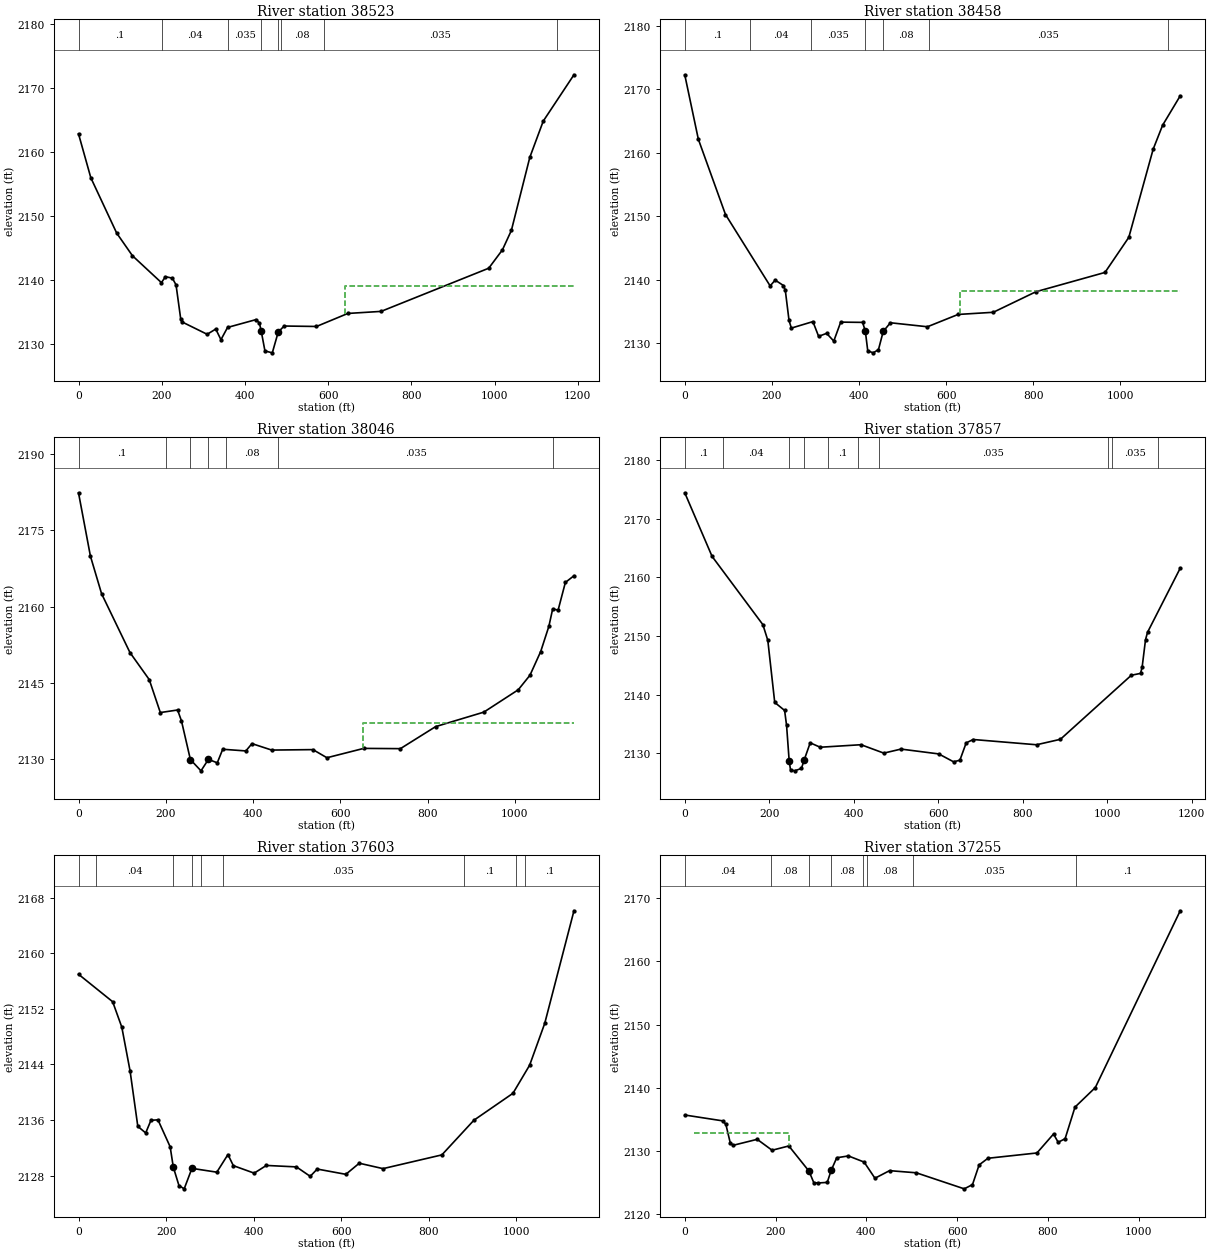
Type RM Length L Ch R = 1 ,38523   ,72.7,64.5,53.4
XS GIS Cut Line= 4
2141715.47845672183294.5209315172142019.02458176183056.445539327
2142179.72547149182990.9748064752142632.06871665182550.535330923
#Sta/Elev= 30
       0 2162.81    29.6 2155.96    91.8 2147.33   129.7  2143.8   199.3 2139.61
   208.9 2140.54   225.6 2140.31   234.4 2139.26   245.6 2133.96   248.4  2133.5
   309.2 2131.56   329.8 2132.38   342.3 2130.72   358.2 2132.63   426.6 2133.85
   434.8  2133.3   439.2 2132.02     448 2128.97   465.7 2128.67   479.9  2131.9
   494.1 2132.85   571.9 2132.78   647.2 2134.81   727.1 2135.13   985.8 2141.86
  1018.7 2144.72  1040.2 2147.75  1084.5 2159.14  1116.8 2164.79  1190.6 2172.01
#Mann= 8 ,-1 , 0
       0      .1       0     200     .04       0     360    .035       0
   439.2    .045       0   479.9    .035       0  485.77     .08       0
   589.3    .035       0  1149.3      .1       0
#XS Ineff= 2 , 0
          433.24 2131.45  641.26         2139.13
Permanent Ineff=
       F       F
Bank Sta=439.2,479.9
XS Rating Curve= 0 ,0
Exp/Cntr(USF)=0,0
Exp/Cntr=0.5,0.3

Type RM Length L Ch R = 1 ,38458   ,409.7,412.7,406
XS GIS Cut Line= 2
     2141809.328      183382.311      2142627.44      182592.089
#Sta/Elev= 30
       0  2172.3    31.2 2162.14    93.5 2150.28     196 2139.03   207.6 2139.94
   226.5 2139.09   230.8 2138.35   239.4 2133.58   244.7 2132.38   294.2  2133.4
   307.3 2131.08   325.7 2131.55   342.1 2130.33     358 2133.32   408.2 2133.28
  414.492131.925   420.1  2128.8   432.6 2128.48   444.7 2128.99   455.62131.848
   472.1 2133.22   557.1 2132.59   627.5 2134.53   708.2 2134.87   806.2 2138.11
   964.7 2141.15  1019.4 2146.68  1075.3 2160.57    1097 2164.35  1137.4 2168.98
#Mann= 7 ,-1 , 0
       0      .1       0     150     .04       0     290    .035       0
  414.49    .045       0   455.6     .08       0     560    .035       0
    1110      .1       0
#XS Ineff= 2 , 0
                          630.95         2138.22
Permanent Ineff=
       F       F
Bank Sta=414.49,455.6
XS Rating Curve= 0 ,0
Exp/Cntr=0.3,0.1

Type RM Length L Ch R = 1 ,38046   ,185.7,189,193.6
XS GIS Cut Line= 3
     2142045.248      183599.542     2142252.376      183414.021
     2142778.332      182736.922
#Sta/Elev= 30
       0 2182.42    27.3 2169.95    52.9 2162.54   117.9 2150.96   162.1 2145.63
   187.5 2139.14   227.1 2139.64     236 2137.48   256.42129.882   280.7 2127.66
   297.72129.923     318 2129.24   330.5 2131.91   383.5 2131.58   397.5 2133.02
   442.7 2131.75   537.2 2131.84   569.3 2130.24   653.6 2132.08   737.7 2132.03
   818.4 2136.37   928.8 2139.22  1007.7 2143.62  1034.6 2146.49  1059.2 2151.16
  1077.9 2156.12  1086.6 2159.54  1099.1 2159.32  1115.7 2164.76  1135.4 2166.08
#Mann= 7 ,-1 , 0
       0      .1       0     200     .04       0   256.4    .045       0
   297.7     .04       0  338.06     .08       0  458.06    .035       0
 1088.06      .1       0
#XS Ineff= 2 , 0
                          651.58         2137.16
Permanent Ineff=
       F       F
Bank Sta=256.4,297.7
XS Rating Curve= 0 ,0
Exp/Cntr=0.3,0.1

Type RM Length L Ch R = 1 ,37857   ,260.6,253.6,246.3
XS GIS Cut Line= 3
2142140.35853862183718.6307225652142837.26599614183179.459520857
2142983.53052427182927.081511547
#Sta/Elev= 30
       02174.411  64.6752163.572  184.972151.934 196.6072149.265 212.977 2138.69
 236.3652137.323 241.0422134.763 247.1912128.709 250.3972127.187 259.9022127.031
 276.2282127.442   282.52128.842 296.9682131.807 320.5582131.052 417.2632131.483
 471.188 2130.05 511.8992130.738 601.2042129.915 636.2842128.572 651.3012128.842
 666.1482131.791  682.742132.371 832.7362131.475 889.2232132.4041057.1182143.319
1078.8222143.6341082.6142144.6471090.7282149.3921095.5292150.6461172.826 2161.56
#Mann= 10 ,-1 , 0
       0      .1       0      90     .04       0 247.191    .045       0
   282.5     .08       0     340      .1       0     410     .08       0
     460    .035       0 1001.13      .1       0 1011.13    .035       0
 1121.13      .1       0
Bank Sta=247.191,282.5
XS Rating Curve= 0 ,0
Exp/Cntr(USF)=0,0
Exp/Cntr=0.3,0.1

Type RM Length L Ch R = 1 ,37603   ,367.9,348.1,324.7
XS GIS Cut Line= 2
     2142419.329      183888.972      2143064.94      182960.145
#Sta/Elev= 30
       0    2157      78 2153.04    98.9 2149.37   117.8 2143.05   135.4 2135.09
   153.4 2134.14   165.4 2135.96   181.4 2136.03   209.3 2132.14   216.42129.232
   229.3 2126.57   241.3 2126.09     2592129.039   315.8 2128.49   341.2 2131.03
   353.5 2129.43   401.1 2128.35   428.9 2129.46   497.6 2129.25     529 2127.89
     545 2128.94   610.4 2128.18     641 2129.78   695.3    2129   829.6 2130.98
   902.7 2135.97   991.9 2139.85    1030  2143.9  1064.4 2149.91  1131.2 2166.14
#Mann= 9 ,-1 , 0
       0      .1       0      40     .04       0   216.4    .045       0
     259     .04       0     280      .1       0     330    .035       0
     880      .1       0    1000    .035       0    1020      .1       0
Bank Sta=216.4,259
XS Rating Curve= 0 ,0
Exp/Cntr=0.5,0.3

Type RM Length L Ch R = 1 ,37255   ,41.3,47.4,44
XS GIS Cut Line= 3
     2142861.551      184047.087     2142876.742      183695.524
     2143197.923      183029.291
#Sta/Elev= 30
       0 2135.67      84 2134.74    90.6 2134.18   100.4 2131.21     107 2130.88
   159.6 2131.82   192.4 2130.09   229.3 2130.77   273.72126.783   284.3 2124.95
   294.2 2124.91   313.9    2125   322.62126.909   334.8  2128.9   360.5 2129.19
   395.1 2128.22     419 2125.66   451.2 2126.86   510.1 2126.52   615.7 2123.98
   633.9 2124.65   648.5 2127.77   667.9 2128.82   775.9 2129.66   812.4 2132.66
   822.7 2131.35   837.9 2131.92   859.7 2136.92   904.5 2140.02  1091.5 2168.01
#Mann= 8 ,-1 , 0
       0     .04       0     190     .08       0   273.7    .045       0
   322.6     .08       0  391.89    .035       0  401.89     .08       0
  501.89    .035       0  861.89      .1       0
#XS Ineff= 3 ,-1
   20.63  228.65 2132.84  233.81  247.56 2129.12  336.96  1091.5 2128.68
Permanent Ineff=
       F       F       F
Bank Sta=273.7,322.6
XS Rating Curve= 0 ,0
Exp/Cntr=0.5,0.3

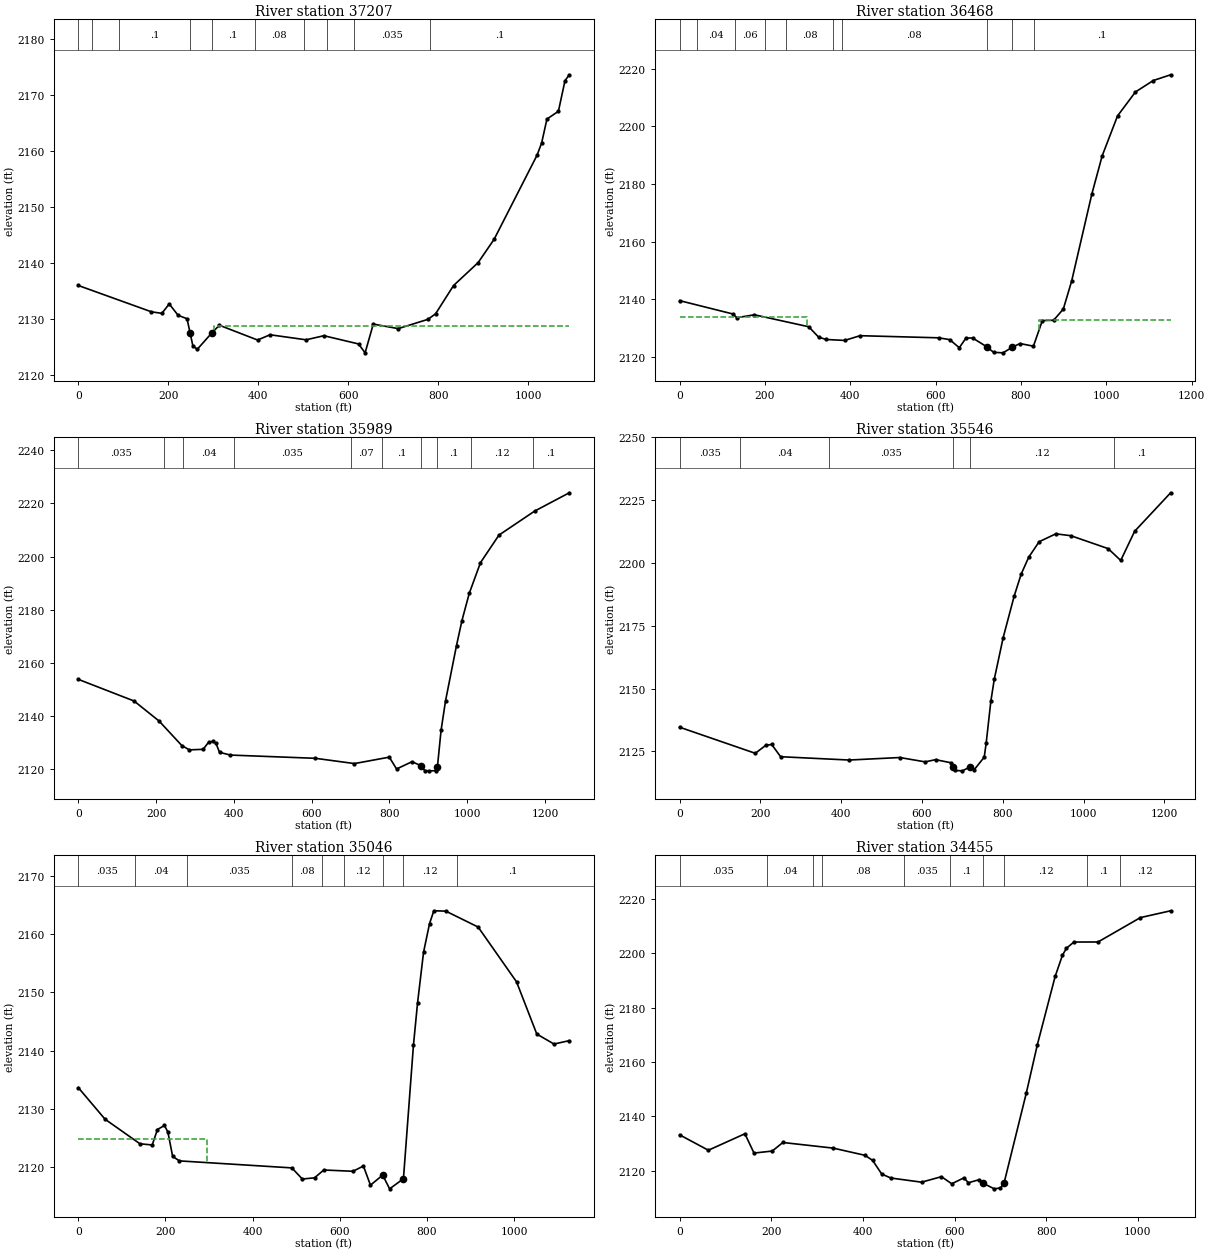
Type RM Length L Ch R = 1 ,37207   ,706.3,739.9,751.3
XS GIS Cut Line= 3
     2142896.273      184047.087     2142911.464      183695.524
     2143232.645      183029.291
#Sta/Elev= 30
       0 2135.94   162.7 2131.23   185.8 2130.96   202.2 2132.64     222  2130.6
   241.7    2130  248.77 2127.39   254.8 2125.12   264.6 2124.54   296.52127.424
   313.7 2128.83   398.6 2126.19   426.3 2127.13   506.4 2126.23     546 2126.96
     623 2125.49   637.6  2123.9   655.8 2129.04   711.2 2128.23     777 2129.88
   794.2 2130.87   834.2 2135.93   888.9 2140.03   924.5 2144.21    1020 2159.25
  1030.1 2161.43  1041.8 2165.69  1067.3 2167.07  1081.9 2172.53  1091.5  2173.6
#Mann= 10 ,-1 , 0
       0     .04       0      30     .06       0      90      .1       0
  248.77    .045       0   296.5      .1       0  391.89     .08       0
  501.89    .035       0  551.89     .08       0  611.89    .035       0
  781.89      .1       0
#XS Ineff= 2 , 0
          240.69 2129.24  300.86         2128.72
Permanent Ineff=
       F       F
Bank Sta=248.77,296.5
XS Rating Curve= 0 ,0
Exp/Cntr=0.5,0.3

Type RM Length L Ch R = 1 ,36468   ,478.3,478.9,477
XS GIS Cut Line= 2
     2142875.692      184155.468     2143592.663      183255.566
#Sta/Elev= 30
       0 2139.58   124.3 2134.97   134.1 2133.67   175.3 2134.67   302.5 2130.52
   325.6 2126.93   343.4  2126.1   386.8 2125.78   422.8 2127.42   607.2 2126.68
   632.9 2126.05   655.3 2123.24   671.1 2126.62   686.6 2126.62   719.9 2123.55
   735.6 2121.65   757.7 2121.47     780 2123.44   797.5  2124.7     829 2123.78
     850 2132.65   876.4 2132.78   899.1 2136.66   918.6 2146.35   965.9 2176.55
   990.1 2189.79  1026.1 2203.65  1068.1 2211.98    1110 2215.95  1150.6 2217.94
#Mann= 10 ,-1 , 0
       0    .035       0      40     .04       0     130     .06       0
     200    .035       0     250     .08       0     360     .07       0
     380     .08       0   719.9    .045       0     780     .08       0
     830      .1       0
#XS Ineff= 2 , 0
          299.14 2133.88  842.41         2133.02
Permanent Ineff=
       F       F
Bank Sta=719.9,780
XS Rating Curve= 0 ,0
Exp/Cntr=0.3,0.1

Type RM Length L Ch R = 1 ,35989   ,444.6,443.1,438.9
XS GIS Cut Line= 2
2143156.87827568 184565.741497432143940.91963831183576.256141371
#Sta/Elev= 30
       0 2153.87   143.5 2145.72   207.9 2138.18   266.5 2128.93   285.9 2127.35
     321 2127.56     335 2130.21   346.1 2130.52   353.7 2129.91   363.2 2126.44
     391  2125.4   609.8 2124.18   710.2  2122.2   799.7 2124.62   818.4 2120.16
   858.1 2122.91   881.22121.406   890.8 2119.55   902.1 2119.47   919.5  2119.5
   923.5 2121.04   932.8 2134.67   944.3 2145.79   972.5 2166.58   986.5 2175.97
  1005.2 2186.16  1034.1 2197.73  1081.7  2208.1  1173.4 2217.12  1262.5 2224.01
#Mann= 10 ,-1 , 0
       0    .035       0     220     .08       0     270     .04       0
     400    .035       0     700     .07       0     780      .1       0
   881.2    .045       0   923.5      .1       0    1010     .12       0
    1170      .1       0
Bank Sta=881.2,923.5
XS Rating Curve= 0 ,0
Exp/Cntr(USF)=0,0
Exp/Cntr=0.3,0.1

Type RM Length L Ch R = 1 ,35546   ,485.6,500,500.9
XS GIS Cut Line= 3
     2143671.786      184779.256     2143989.686      184161.363
     2144304.689      183746.634
#Sta/Elev= 30
       0 2134.64   187.3 2124.26   213.3 2127.44   227.9 2127.78     250  2122.9
   419.7 2121.58   545.2 2122.58   607.9 2120.85   633.7 2121.73   671.3 2120.51
  676.582118.724   681.1 2117.43   700.3 2117.28   717.82118.763   729.6 2117.78
   754.1 2122.71   758.9 2128.21   770.6 2145.05     779 2153.74     801 2170.27
   828.4 2186.89   845.5 2195.53   864.2 2202.28   890.2 2208.48   931.4 2211.61
   968.5 2210.87  1060.9 2205.73  1092.1 2201.01  1126.5 2212.61  1215.7 2227.95
#Mann= 6 ,-1 , 0
       0    .035       0     150     .04       0     370    .035       0
  676.58    .045       0   717.8     .12       0 1074.88      .1       0
Bank Sta=676.58,717.8
XS Rating Curve= 0 ,0
Exp/Cntr=0.3,0.1

Type RM Length L Ch R = 1 ,35046   ,566.5,590.8,587.2
XS GIS Cut Line= 3
     2143781.599      184870.676     2144369.775      184458.198
     2144660.857      184171.462
#Sta/Elev= 30
       0 2133.68    61.5 2128.26   141.6 2124.05   169.7 2123.85   181.7  2126.5
   197.8 2127.19   205.7 2126.06   216.6 2121.89   232.1 2121.12   490.2 2119.92
   514.3 2118.01   542.3 2118.22   563.5 2119.56   630.5 2119.34   654.5 2120.24
   670.6 2116.96   698.72118.682   714.6 2116.33  746.32 2118.06   769.3 2140.95
   778.7 2148.18   792.5 2156.89   806.2 2161.78   816.1 2163.99   843.6 2163.93
   917.8  2161.2    1006  2151.8  1052.4 2142.86  1091.9 2141.15    1127 2141.73
#Mann= 9 ,-1 , 0
       0    .035       0     130     .04       0     250    .035       0
     490     .08       0     560    .035       0     610     .12       0
   698.7    .045       0  746.32     .12       0  868.39      .1       0
#XS Ineff= 2 , 0
          295.98  2124.8
Permanent Ineff=
       F       F
Bank Sta=698.7,746.32
XS Rating Curve= 0 ,0
Exp/Cntr=0.3,0.1

Type RM Length L Ch R = 1 ,34455   ,405.9,409.2,414.5
XS GIS Cut Line= 2
     2143891.329      184991.395     2144950.541       184828.87
#Sta/Elev= 30
       0 2133.22    62.7 2127.56   142.4 2133.62   162.3 2126.52   202.1 2127.26
   225.3 2130.41   335.2 2128.34   404.6 2125.69   421.2 2123.82   441.1 2118.79
     461 2117.34   528.1 2115.81   571.4 2117.84   593.8 2115.22   620.3 2117.39
   630.3  2115.6   653.5 2116.72     6622115.446   686.7 2113.36     700 2113.69
   707.8 2115.34   756.4 2148.46   780.7 2166.38   819.5 2191.48   835.4 2199.26
     844 2201.84   860.5 2204.15   913.1 2204.17  1005.6 2213.14  1071.6 2215.65
#Mann= 10 ,-1 , 0
       0    .035       0     190     .04       0     290     .06       0
     310     .08       0     490    .035       0     590      .1       0
     662    .045       0   707.8     .12       0     890      .1       0
     960     .12       0
Bank Sta=662,707.8
XS Rating Curve= 0 ,0
Exp/Cntr=0.3,0.1