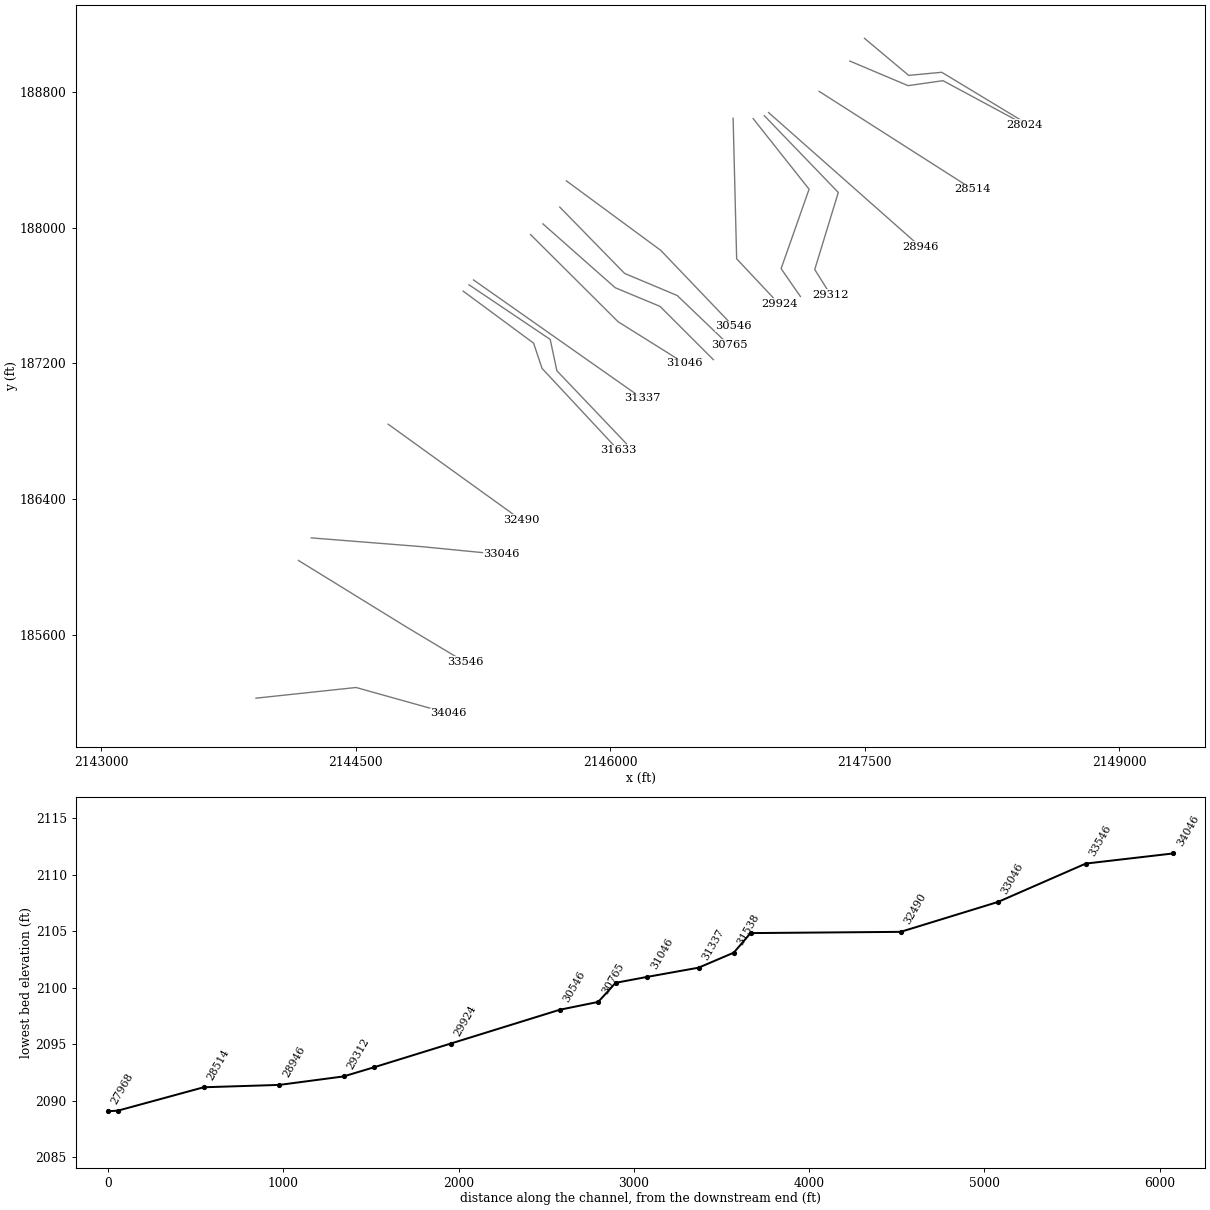
HEC-RAS study POTTSCK.prj: POTTSCK

--- POTTSCK.g01 (geometry) --- (continued)

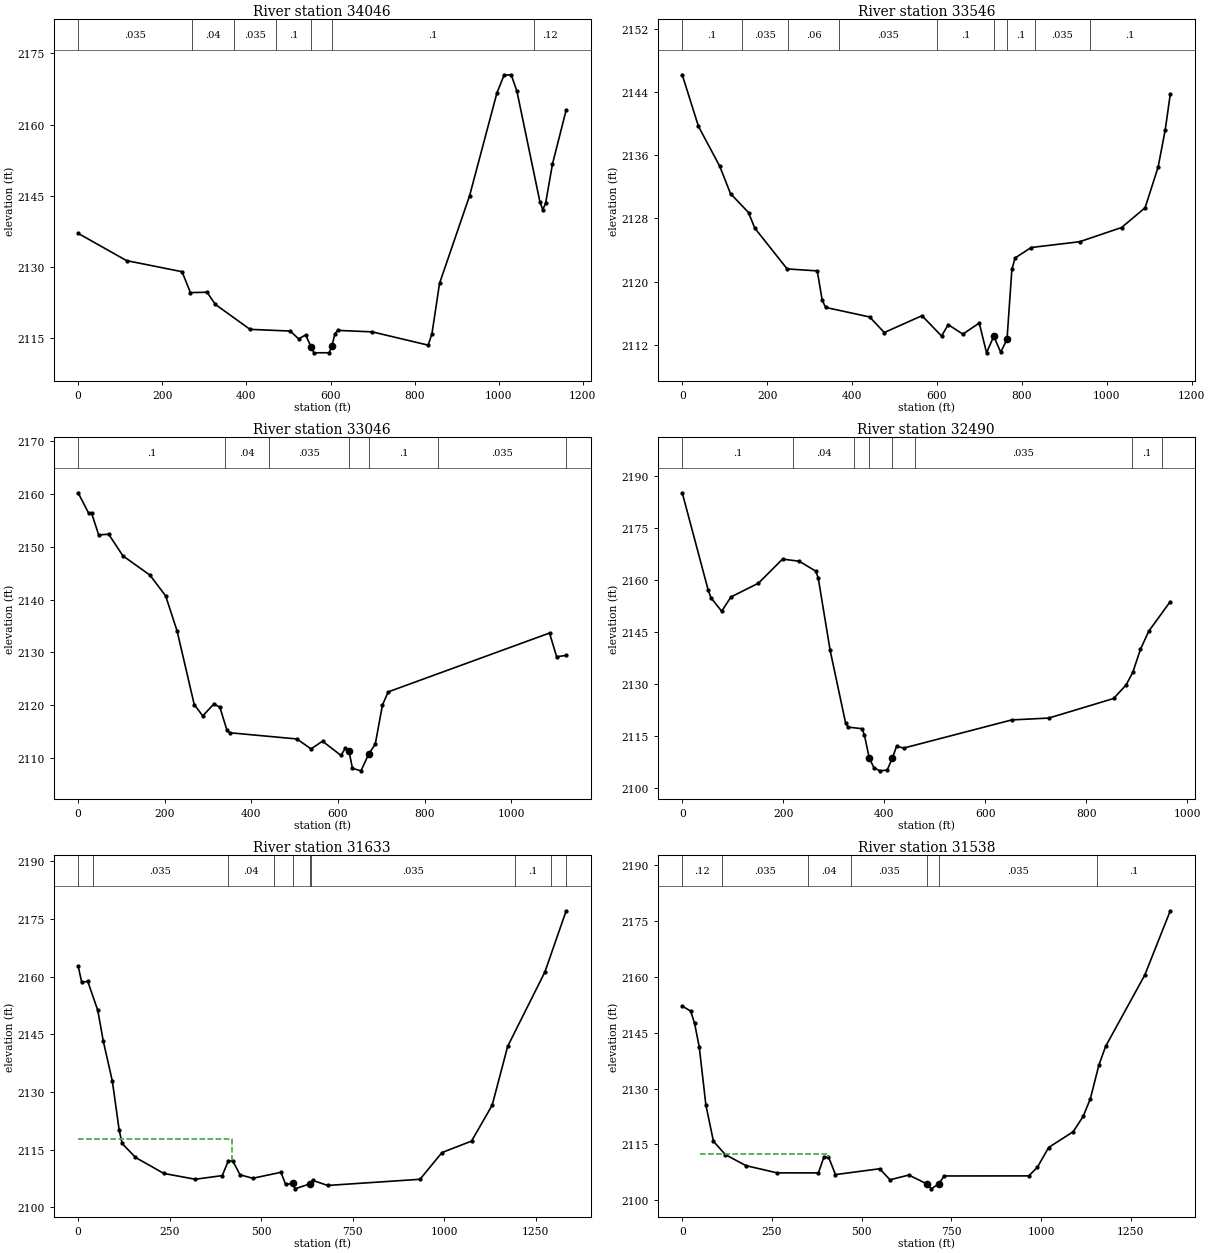
Type RM Length L Ch R = 1 ,34046   ,531.6,500,497
XS GIS Cut Line= 3
     2143911.067      185224.471      2144501.11      185287.538
     2145047.016      185134.799
#Sta/Elev= 30
       0 2137.08   115.1 2131.33   247.1 2128.99   266.9 2124.59   306.5 2124.66
   326.3 2122.09   408.7 2116.84   504.4 2116.48   524.2 2114.83   540.7 2115.66
   554.12113.119   560.5 2111.89   596.9 2111.91   603.22113.325   610.6 2115.93
   617.4 2116.62   699.1 2116.31   832.2 2113.51   841.1 2115.88   859.2 2126.53
   930.7 2145.01   995.5 2166.62  1012.6 2170.42  1029.6  2170.5  1043.2 2167.02
  1097.7 2143.78  1104.5 2142.07  1111.4 2143.41  1127.7 2151.69  1160.3 2163.08
#Mann= 7 ,-1 , 0
       0    .035       0     270     .04       0     370    .035       0
     470      .1       0   554.1    .045       0   603.2      .1       0
  1083.4     .12       0
Bank Sta=554.1,603.2
XS Rating Curve= 0 ,0
Exp/Cntr=0.3,0.1

Type RM Length L Ch R = 1 ,33546   ,484.2,500,505.2
XS GIS Cut Line= 3
     2144161.619      186037.057     2144800.086      185643.415
     2145142.603      185437.908
#Sta/Elev= 30
       0 2146.18    38.3 2139.64    88.3 2134.61   113.7 2131.14   156.1 2128.75
   170.8 2126.78   247.1 2121.61     318 2121.36   329.6 2117.67   337.7 2116.74
   441.4 2115.53   475.9 2113.56   564.7 2115.69   610.9 2113.12   626.4 2114.56
     661 2113.36   699.6 2114.76   716.8 2110.99   733.72113.085   750.1 2111.07
  764.992112.719   776.4 2121.55   784.1    2123   821.9 2124.32   935.9 2125.05
  1034.8 2126.85  1090.2 2129.35  1120.9 2134.51  1137.6  2139.2  1149.5 2143.73
#Mann= 9 ,-1 , 0
       0      .1       0     140    .035       0     250     .06       0
     370    .035       0     600      .1       0   733.7    .045       0
  764.99      .1       0  830.06    .035       0  960.06      .1       0
Bank Sta=733.7,764.99
XS Rating Curve= 0 ,0
Exp/Cntr=0.3,0.1

Type RM Length L Ch R = 1 ,33046   ,567.5,555.9,538.3
XS GIS Cut Line= 3
     2144237.388      186170.241     2144886.676      186118.708
     2145359.783      186072.233
#Sta/Elev= 30
       0 2160.19    24.4  2156.3      31 2156.37    47.4 2152.22    70.5 2152.35
   103.4 2148.26   165.9 2144.61   202.1 2140.68   228.5 2134.04     268 2120.14
   287.7 2117.99   313.5 2120.26   327.2 2119.62   343.6 2115.28   350.2  2114.8
   504.9 2113.63   537.8 2111.75   564.2 2113.21   606.9 2110.51   616.8  2111.9
   625.22111.365   633.3 2108.07     653  2107.6     6712110.799     686 2112.66
   702.5 2120.02   715.7 2122.53  1088.2 2133.66  1104.7 2129.18  1126.7 2129.43
#Mann= 7 ,-1 , 0
       0      .1       0     340     .04       0     440    .035       0
   625.2    .045       0     671      .1       0  831.33    .035       0
 1126.71      .1       0
Bank Sta=625.2,671
XS Rating Curve= 0 ,0
Exp/Cntr=0.3,0.1

Type RM Length L Ch R = 1 ,32490   ,870.3,856.3,834.9
XS GIS Cut Line= 2
     2144690.459      186841.026     2145474.293      186276.204
#Sta/Elev= 30
       0 2185.13    51.5    2157    57.1 2154.79    78.1 2150.97    96.4 2155.09
   150.9 2159.06   198.6 2166.01   231.8 2165.38   264.1 2162.55   269.1 2160.65
   292.8 2139.68   323.2 2118.87   327.9 2117.56   356.1  2117.1   360.8 2115.18
   370.1 2108.68   379.6 2105.81   391.3 2104.95   405.7 2105.18   415.92108.591
   424.2    2112   438.8 2111.53   652.2 2119.63   725.6 2120.17     854 2125.81
   878.8 2129.76   891.9 2133.36   907.1    2140   923.3 2145.17   966.1 2153.76
#Mann= 8 ,-1 , 0
       0      .1       0     220     .04       0     340    .035       0
   370.1    .045       0   415.9     .08       0     460    .035       0
     890      .1       0     950    .035       0
Bank Sta=370.1,415.9
XS Rating Curve= 0 ,0
Exp/Cntr=0.3,0.1

Type RM Length L Ch R = 1 ,31633   ,101.9,95.6,91.8
XS GIS Cut Line= 4
2145133.03713358187626.0179021722145548.19946872187319.238654519
2145597.79850876187170.4415344012146047.86387209186687.310144385
#Sta/Elev= 30
       0 2162.76     9.9 2158.48    26.2 2158.78    53.7 2151.21    68.7 2143.23
    93.5 2132.82   111.9 2120.25     120 2116.65   156.7    2113   234.2 2108.84
   319.9 2107.33   393.8 2108.28   409.7 2111.98     422 2112.19   442.3 2108.48
   477.2 2107.59   554.1 2109.14   566.8 2105.99   587.12106.241   592.1 2104.84
   632.5 2106.11   640.5 2107.06   681.5 2105.72   933.9 2107.32     994 2114.27
  1074.8 2117.25  1131.2 2126.59  1173.4 2141.86  1275.1 2161.18  1333.3  2177.1
#Mann= 10 ,-1 , 0
       0     .12       0      40    .035       0     410     .04       0
  536.21     .06       0   587.1    .045       0   632.5     .06       0
  636.21    .035       0 1193.06      .1       0 1293.06    .035       0
 1333.06      .1       0
#XS Ineff= 2 , 0
           421.2  2117.7  639.83         2106.07
Permanent Ineff=
       F       F
Bank Sta=587.1,632.5
XS Rating Curve= 0 ,0
Exp/Cntr(USF)=0,0
Exp/Cntr=0.5,0.3

Type RM Length L Ch R = 1 ,31538   ,177.9,200.9,217.2
XS GIS Cut Line= 4
2145167.20700213 187663.518422092145646.18098079187341.096249684
2145685.31893235187156.5887637412146095.33556778 186726.07129654
#Sta/Elev= 30
       0 2152.11    23.8 2150.73    34.5 2147.43    47.5  2141.1    65.9 2125.59
      87 2115.85   120.3 2112.27     178 2109.32   264.5 2107.39   379.7 2107.38
   394.5 2111.52   407.4 2111.75   427.2 2106.93   550.5 2108.49   579.1 2105.53
   631.7 2106.81   683.4 2104.36   694.8 2103.11   715.72104.523   730.3 2106.56
   966.2 2106.58     990 2108.89  1021.4 2114.19  1089.9 2118.43  1117.5  2122.5
  1137.5 2127.21  1161.5 2136.28  1180.1 2141.27  1289.2 2160.37  1360.5 2177.64
#Mann= 7 ,-1 , 0
       0     .12       0     110    .035       0     350     .04       0
     470    .035       0   683.4    .045       0   715.7    .035       0
    1156      .1       0
#XS Ineff= 3 ,-1
   50.14  405.16 2112.39  441.26  673.93 2104.55  721.12  1360.5 2104.59
Permanent Ineff=
       F       F       F
Bank Sta=683.4,715.7
XS Rating Curve= 0 ,0
Exp/Cntr(USF)=0,0
Exp/Cntr=0.5,0.3

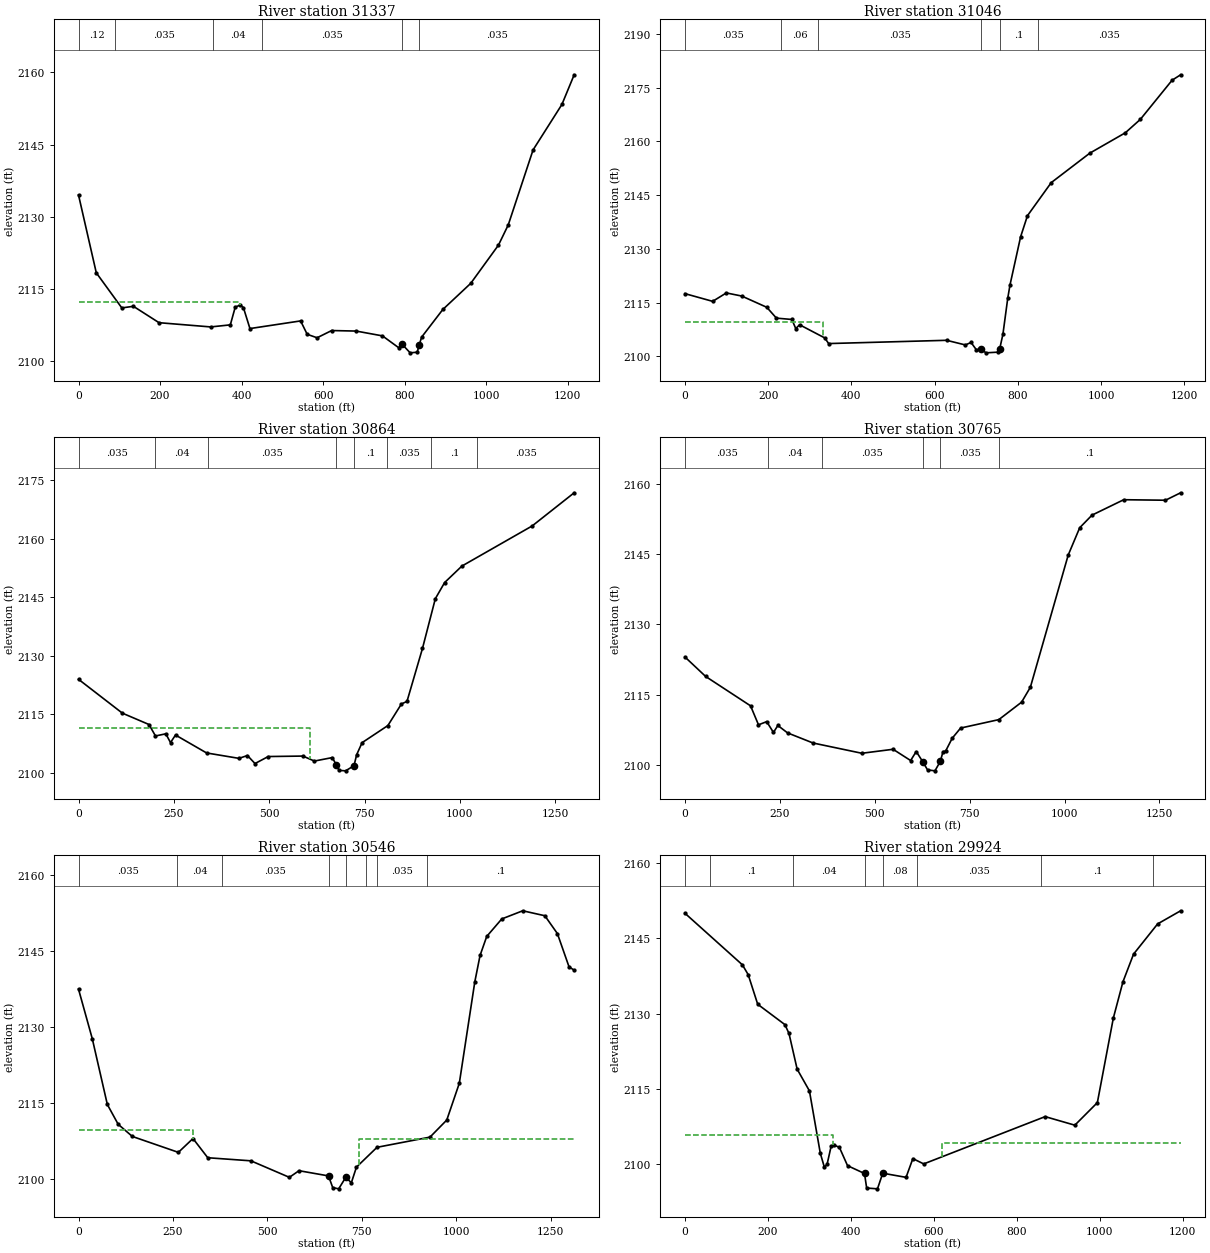
Type RM Length L Ch R = 1 ,31337   ,295.1,291.4,292.9
XS GIS Cut Line= 2
     2145193.902      187692.169     2146188.593      186993.103
#Sta/Elev= 30
       0 2134.56    43.6  2118.4   106.2 2111.11   134.7 2111.44   197.5 2108.04
   324.3 2107.16   372.4 2107.59   384.4 2111.27   396.8 2111.71   404.5 2111.17
   420.5 2106.82   544.8 2108.41   560.9 2105.63   585.2 2104.91     621 2106.41
   681.2  2106.3   745.6  2105.3   785.3 2102.85     7932103.631   813.5 2101.78
   830.8 2101.91   835.62103.385   841.6 2105.04   893.7 2110.79   962.1 2116.21
  1030.1 2124.15  1054.1 2128.34    1115 2143.92  1185.7 2153.35  1215.8 2159.52
#Mann= 6 ,-1 , 0
       0     .12       0      90    .035       0     330     .04       0
     450    .035       0     793    .045       0   835.6    .035       0
#XS Ineff= 2 , 0
          396.73 2112.36
Permanent Ineff=
       F       F
Bank Sta=793,835.6
XS Rating Curve= 0 ,0
Exp/Cntr=0.3,0.1

Type RM Length L Ch R = 1 ,31046   ,174,182,187.9
XS GIS Cut Line= 3
     2145529.922      187960.191      2146046.03      187445.797
     2146437.994      187200.276
#Sta/Elev= 30
       0  2117.5    66.5 2115.35    99.4  2117.7   136.4 2116.83   196.6 2113.69
   219.8 2110.66   256.9 2110.29   266.2 2107.75   275.5 2108.81   335.8 2105.14
   345.3 2103.56   628.8 2104.47   673.7 2103.18   687.6 2103.86     700 2101.86
   712.3 2102.03   723.2 2100.97   751.7 2101.16   756.3 2102.05   764.1 2106.15
   775.7 2116.22   781.3 2120.03   806.6 2133.37   823.1 2139.27   880.2  2148.5
   972.9 2156.73  1058.3 2162.42  1094.4 2166.17  1170.6 2177.09  1191.2 2178.62
#Mann= 6 ,-1 , 0
       0    .035       0     230     .06       0     320    .035       0
   712.3    .045       0   756.3      .1       0  848.68    .035       0
#XS Ineff= 2 , 0
          332.62 2109.55
Permanent Ineff=
       F       F
Bank Sta=712.3,756.3
XS Rating Curve= 0 ,0
Exp/Cntr=0.5,0.3

Type RM Length L Ch R = 1 ,30864   ,99.4,99,99.2
XS GIS Cut Line= 4
2145603.30951321188022.8102224892146029.49385726187646.224918484
 2146294.0220708187536.0048295072146608.14932439187221.877575923
#Sta/Elev= 30
       0 2123.93     115 2115.24   184.7 2112.33   201.8 2109.39   228.9 2109.94
   241.2 2107.69   254.3 2109.63   335.8 2105.03   420.7 2103.64   442.9 2104.37
   462.7 2102.31   497.4 2104.11   588.3 2104.23   618.4 2102.95   665.3 2103.84
   676.3 2101.92   683.1 2100.56   700.2 2100.44   722.2 2101.75   729.3 2104.59
   743.5 2107.67   811.1 2112.06   846.6  2117.6   861.2 2118.26   901.8 2131.85
   935.5 2144.61   959.9 2148.76  1005.1 2152.98  1189.4 2163.28  1299.5 2171.79
#Mann= 8 ,-1 , 0
       0    .035       0     200     .04       0     340    .035       0
   676.3    .045       0   722.2      .1       0  808.73    .035       0
   925.3      .1       0  1045.3    .035       0
#XS Ineff= 2 , 0
          607.74 2111.45   736.1          2102.6
Permanent Ineff=
       F       F
Bank Sta=676.3,722.2
XS Rating Curve= 0 ,0
Exp/Cntr(USF)=0,0
Exp/Cntr=0.5,0.3

Type RM Length L Ch R = 1 ,30765   ,224.1,219,207.6
XS GIS Cut Line= 4
2145702.50759329188122.0083025682146084.60390174  187730.7269867
2146395.05715236187600.2998814112146699.99939853187308.216645622
#Sta/Elev= 30
       0 2123.04    54.5 2118.89   172.8 2112.62   193.7 2108.57   215.3 2109.25
   233.1 2106.94   244.7 2108.43   270.2 2106.85   337.4 2104.69     466  2102.5
   548.3 2103.35   594.5 2100.95   609.3 2102.87   626.8 2100.65   639.1 2098.95
   658.6 2098.75   672.8 2100.78   679.9 2102.85   686.6 2102.95   704.1 2105.71
   726.2 2107.88   826.9 2109.68   886.8  2113.4     910 2116.59  1009.7  2144.8
    1040 2150.63  1072.4 2153.32    1156 2156.61    1266  2156.5  1305.9 2158.09
#Mann= 6 ,-1 , 0
       0    .035       0     220     .04       0     360    .035       0
   626.8    .045       0   672.8    .035       0   826.9      .1       0
#XS Ineff= 2 , 0
          617.77 2101.24  679.94         2101.24
Permanent Ineff=
       F       F
Bank Sta=626.8,672.8
XS Rating Curve= 0 ,0
Exp/Cntr(USF)=0,0
Exp/Cntr=0.5,0.3

Type RM Length L Ch R = 1 ,30546   ,643,621.6,600.1
XS GIS Cut Line= 3
     2145741.549       188276.76     2146297.951      187866.671
     2146726.752      187417.891
#Sta/Elev= 30
       0 2137.48    36.5 2127.68    76.3 2114.71     105  2110.8   142.5  2108.4
   264.3 2105.26     303 2107.99   342.1  2104.2   456.3 2103.59   558.1 2100.33
   583.6 2101.64   661.72100.614   672.8 2098.31   688.6 2098.06   707.52100.349
   722.1 2099.25   735.6 2102.34   790.1 2106.26   930.3 2108.27   974.7 2111.64
  1007.9  2118.9  1048.9 2138.92  1062.8 2144.13  1080.5 2147.89  1120.3 2151.34
  1175.8 2152.95  1234.3 2151.97  1267.5 2148.45  1298.3 2141.89  1311.9 2141.22
#Mann= 8 ,-1 , 0
       0    .035       0     260     .04       0     380    .035       0
   661.7    .045       0   707.5    .035       0   761.2     .08       0
   791.2    .035       0   921.2      .1       0
#XS Ineff= 2 , 0
          301.96 2109.75  742.62         2107.85
Permanent Ineff=
       F       F
Bank Sta=661.7,707.5
XS Rating Curve= 0 ,0
Exp/Cntr=0.3,0.1

Type RM Length L Ch R = 1 ,29924   ,440.9,435.8,416.5
XS GIS Cut Line= 3
     2146724.656      188646.302     2146745.495      187816.915
     2146995.543      187550.197
#Sta/Elev= 30
       0 2150.01   138.5 2139.73   152.4 2137.78   175.4 2131.87     241 2127.81
   250.8 2126.05   270.5 2118.93   300.1  2114.6   326.3 2102.17   336.2 2099.36
   342.7 2099.97   352.6 2103.62   359.1  2103.8   372.3 2103.35     392 2099.69
   432.92098.129   438.1 2095.23   464.2 2095.07   476.92098.187   533.1 2097.36
   549.5  2101.1   575.7 2100.04   868.5 2109.47   940.1 2107.76   994.4 2112.26
  1032.9 2129.11  1056.1 2136.35  1081.7 2141.87  1139.7 2147.89  1195.2 2150.51
#Mann= 8 ,-1 , 0
       0    .035       0      60      .1       0     260     .04       0
   432.9    .045       0   476.9     .08       0     560    .035       0
  859.65      .1       0 1129.65     .12       0
#XS Ineff= 2 , 0
          357.89 2105.73   619.2         2104.19
Permanent Ineff=
       F       F
Bank Sta=432.9,476.9
XS Rating Curve= 0 ,0
Exp/Cntr=0.5,0.3

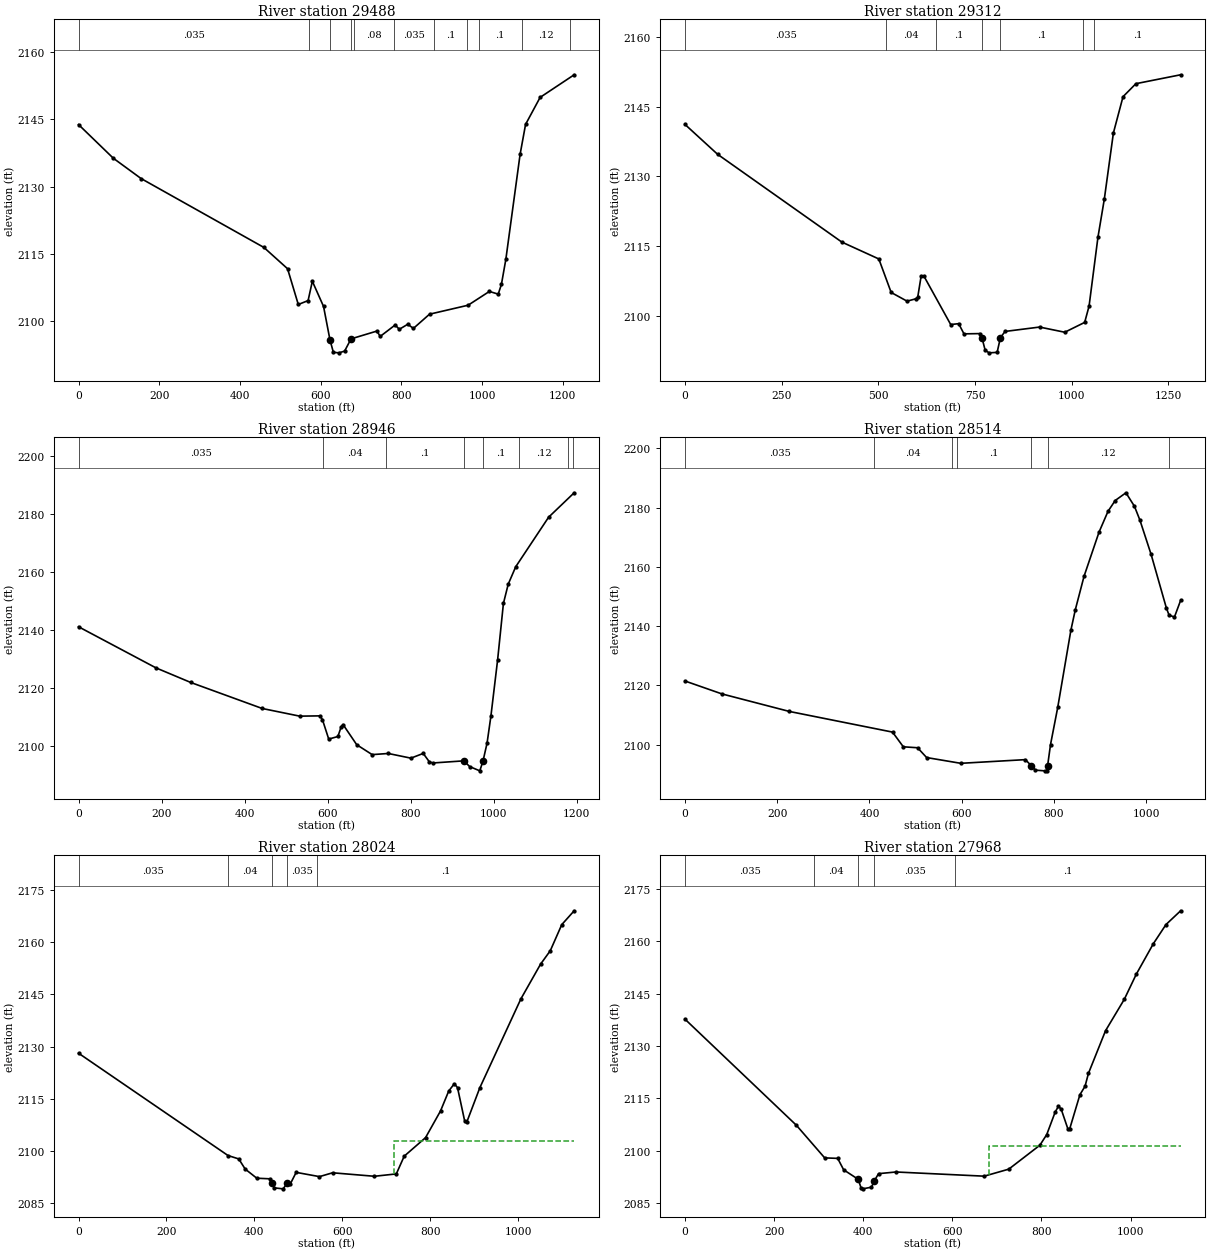
Type RM Length L Ch R = 1 ,29488   ,175,176,177.2
XS GIS Cut Line= 4
     2146842.718      188644.172     2147172.579      188227.506
     2147007.648      187758.756     2147121.382      187594.474
#Sta/Elev= 30
       0 2143.84    86.2 2136.34   154.9 2131.82   459.4 2116.46     518 2111.72
   544.6 2103.75   568.9 2104.62   579.4 2108.93   607.2 2103.31     6232095.911
   631.5 2093.09   645.4 2092.98   659.4 2093.37   675.32096.093   739.4 2097.83
   747.6 2096.64   784.6 2099.18     795 2098.23   815.9 2099.35   829.8 2098.42
   869.8 2101.59   965.4 2103.59  1018.1 2106.66    1040 2106.06  1047.9 2108.22
  1058.9 2113.81  1094.2 2137.19  1107.8 2143.88  1143.8 2149.89  1228.2 2154.93
#Mann= 11 ,-1 , 0
       0    .035       0  571.43     .04       0     623    .045       0
   675.3     .04       0  681.43     .08       0  781.43    .035       0
  881.43      .1       0  961.43    .035       0  991.43      .1       0
 1098.35     .12       0 1218.35      .1       0
#XS Ineff= 2 , 0
          597.71 2096.98  714.04         2096.83
Permanent Ineff=
       F       F
Bank Sta=623,675.3
XS Rating Curve= 0 ,0
Exp/Cntr=0.5,0.3

Type RM Length L Ch R = 1 ,29312   ,324.8,366.1,389.4
XS GIS Cut Line= 4
 2146908.3545534188661.4707152272147344.82610575188208.466149532
2147205.94879364187753.8082825022147300.18696971187603.357861049
#Sta/Elev= 30
       0 2141.16    84.4 2134.75   405.7 2115.92   501.4  2112.3   533.3 2105.11
   574.3 2103.25   597.2 2103.75     602  2104.1   610.7 2108.56     618 2108.62
   687.3 2098.23   707.9 2098.42   721.6 2096.23   762.8 2096.29   768.6 2095.25
   776.5 2092.69   786.8 2092.16   807.4 2092.26   815.82095.404   827.8 2096.75
   917.2 2097.69   982.3 2096.58  1033.8 2098.69  1045.2  2102.2  1068.1 2116.94
  1084.7 2125.18  1108.1 2139.33    1133 2147.11  1166.3  2149.9    1282 2151.81
#Mann= 7 ,-1 , 0
       0    .035       0     520     .04       0  649.06      .1       0
   768.6    .045       0   815.8      .1       0 1029.06    .035       0
 1059.06      .1       0
#XS Ineff= 2 , 0
           736.1 2095.47  826.36         2095.77
Permanent Ineff=
       F       F
Bank Sta=768.6,815.8
XS Rating Curve= 0 ,0
Exp/Cntr(USF)=0,0
Exp/Cntr=0.5,0.3

Type RM Length L Ch R = 1 ,28946   ,422.4,431.8,432.2
XS GIS Cut Line= 2
     2146933.575      188679.851     2147827.675      187888.917
#Sta/Elev= 30
       0 2141.05   186.7 2126.87   270.2 2121.86   442.2  2112.9   532.7 2110.25
   581.7 2110.35   587.6 2108.99   602.6 2102.35   624.7 2103.24   632.8 2106.67
   637.1 2107.36     670 2100.41   707.2    2097     746 2097.39   800.5 2095.78
   830.2 2097.41     845 2094.49   853.6 2094.12   928.12094.854     942 2092.88
   966.4 2091.41     9742094.684   983.9 2100.94   993.1 2110.17  1009.4 2129.71
  1023.3 2149.07  1034.9 2155.72    1053 2161.73  1132.2 2178.79  1193.7  2187.2
#Mann= 8 ,-1 , 0
       0    .035       0     590     .04       0     740      .1       0
   928.1    .045       0     974      .1       0    1060     .12       0
    1180      .1       0    1190     .12       0
Bank Sta=928.1,974
XS Rating Curve= 0 ,0
Exp/Cntr=0.3,0.1

Type RM Length L Ch R = 1 ,28514   ,465.9,489.7,498.8
XS GIS Cut Line= 2
2147232.21626758188804.5961371572148137.84693245188225.998767936
#Sta/Elev= 30
       0 2121.51    80.2 2117.15   226.3 2111.24     450 2104.27   473.4 2099.31
   504.3 2098.99     524 2095.68     598 2093.74   738.1 2094.98   751.3 2092.87
   759.8 2091.43   779.8  2091.2   784.6 2091.27   786.1 2092.74   792.6 2100.08
   808.2 2112.59   836.8 2138.69   846.3 2145.53   865.3 2156.86   897.7 2171.71
   917.2 2178.75   932.8 2182.41   956.1 2185.02   974.6 2180.45   986.5 2175.75
  1010.7 2164.22  1043.5 2146.29  1049.6 2143.72  1061.3  2143.1  1074.7 2148.71
#Mann= 7 ,-1 , 0
       0    .035       0     410     .04       0     580    .035       0
     590      .1       0   751.3    .045       0   786.1     .12       0
    1050      .1       0
Bank Sta=751.3,786.1
XS Rating Curve= 0 ,0
Exp/Cntr(USF)=0,0
Exp/Cntr=0.3,0.1

Type RM Length L Ch R = 1 ,28024   ,57.7,56.8,55.5
XS GIS Cut Line= 4
2147412.81232464188983.6006691372147756.33160196188838.477551985
2147962.07576805188867.8695757122148443.37015658188608.852366616
#Sta/Elev= 30
       0  2128.1     340  2098.7   364.5 2097.72     379 2094.82   405.5 2092.18
   435.4 2092.01   439.1 2090.94   445.3 2089.41   465.2 2089.13   475.1 2090.77
   481.8 2090.56     495 2093.86     548 2092.64   577.9 2093.74     673 2092.74
   722.8 2093.42   740.8 2098.52   789.3 2103.84   823.4 2111.52     842 2117.23
   854.7 2119.32     862  2118.2   878.2 2108.66     883 2108.28   912.8 2118.19
    1006 2143.67  1050.9 2153.68    1073 2157.54  1099.1 2165.03  1127.3 2169.01
#Mann= 5 ,-1 , 0
       0    .035       0     340     .04       0   439.1    .045       0
   475.1    .035       0  542.92      .1       0
#XS Ineff= 3 ,-1
       0   421.2 2091.28  488.25  616.08 2092.01  716.44 1213.242102.831
Permanent Ineff=
       F       F       F
Bank Sta=439.1,475.1
XS Rating Curve= 0 ,0
Exp/Cntr(USF)=0,0
Exp/Cntr=0.5,0.3

Type RM Length L Ch R = 1 ,27968   ,130.5,117.8,101.2
XS GIS Cut Line= 4
2147499.15139434189117.7017773932147760.00560492188899.098600922
2147954.72776211188917.4686157512148447.93838321188619.162683501
#Sta/Elev= 30
       0  2137.7     250  2107.3   313.5 2097.95   342.7 2097.81   356.1 2094.53
   388.8 2091.81   395.4 2089.25   398.7 2089.08   418.5 2089.55   425.1 2091.42
   434.4 2093.43   473.5 2093.91   671.5 2092.71   726.6 2094.72   796.4 2101.58
   811.8 2104.62   830.9 2111.13     838  2112.7   844.1 2111.97   859.4 2106.21
   863.3 2106.25   886.3 2116.06   897.8 2118.48   905.4 2122.16   943.8  2134.4
   985.9 2143.39  1012.8 2150.59  1051.1 2159.33  1079.4 2164.81  1112.3 2168.76
#Mann= 5 ,-1 , 0
       0    .035       0     290     .04       0   388.8    .045       0
   425.1    .035       0  605.93      .1       0
#XS Ineff= 2 , 0
          373.07 2091.93  681.36         2101.25
Permanent Ineff=
       F       F
Bank Sta=388.8,425.1
XS Rating Curve= 0 ,0
Exp/Cntr(USF)=0,0
Exp/Cntr=0.5,0.3