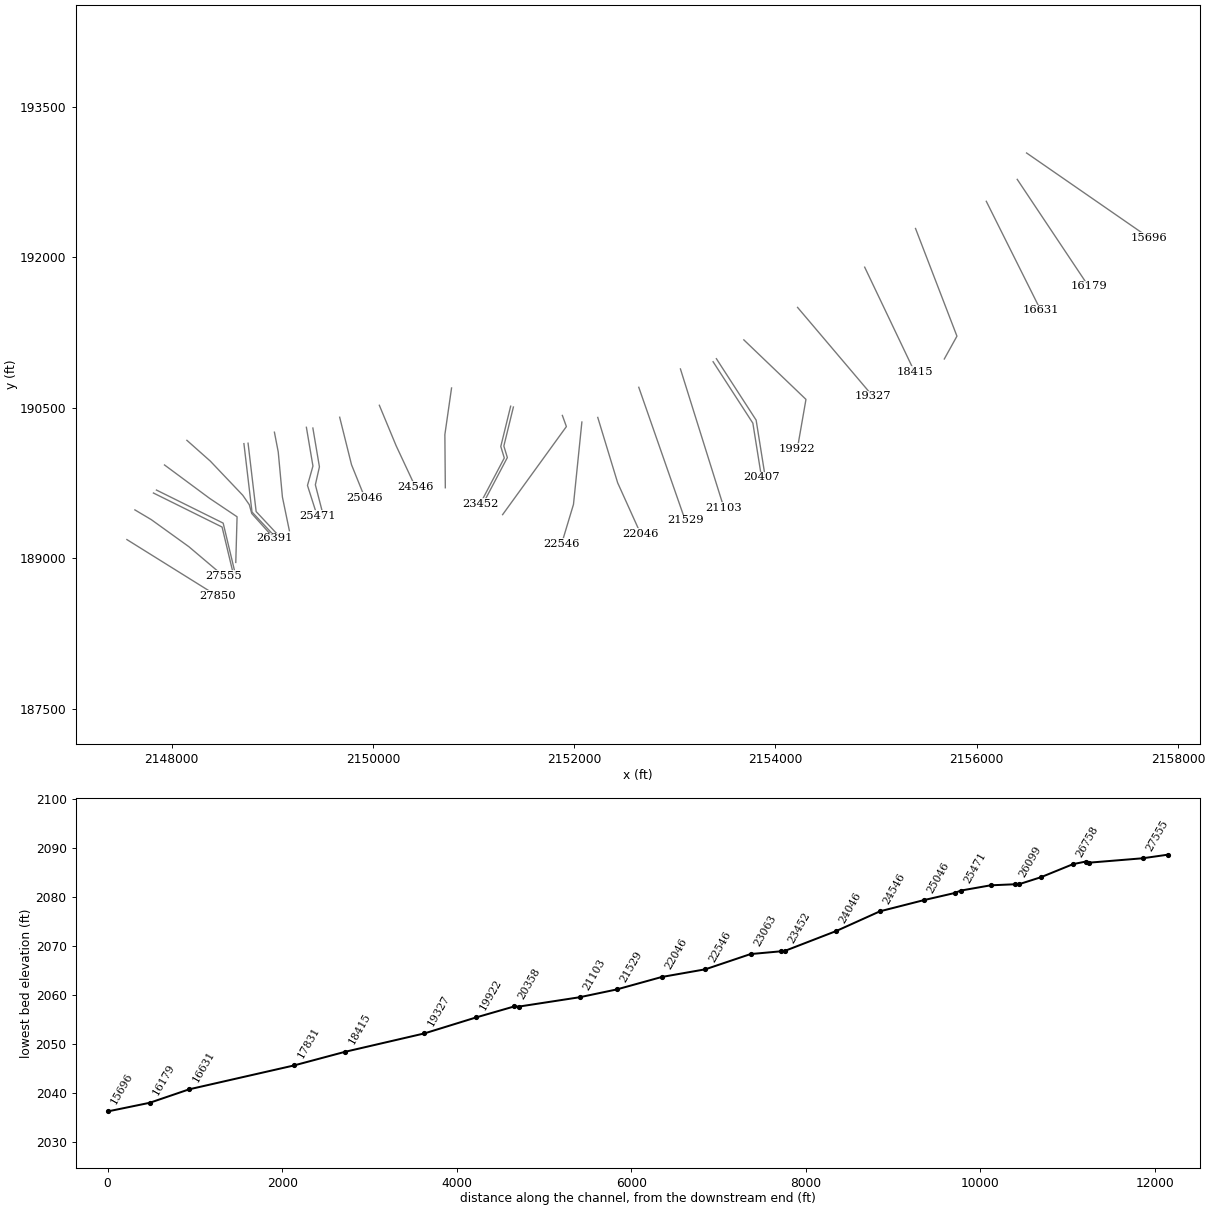
HEC-RAS study POTTSCK.prj: POTTSCK

--- POTTSCK.g01 (geometry) --- (continued)

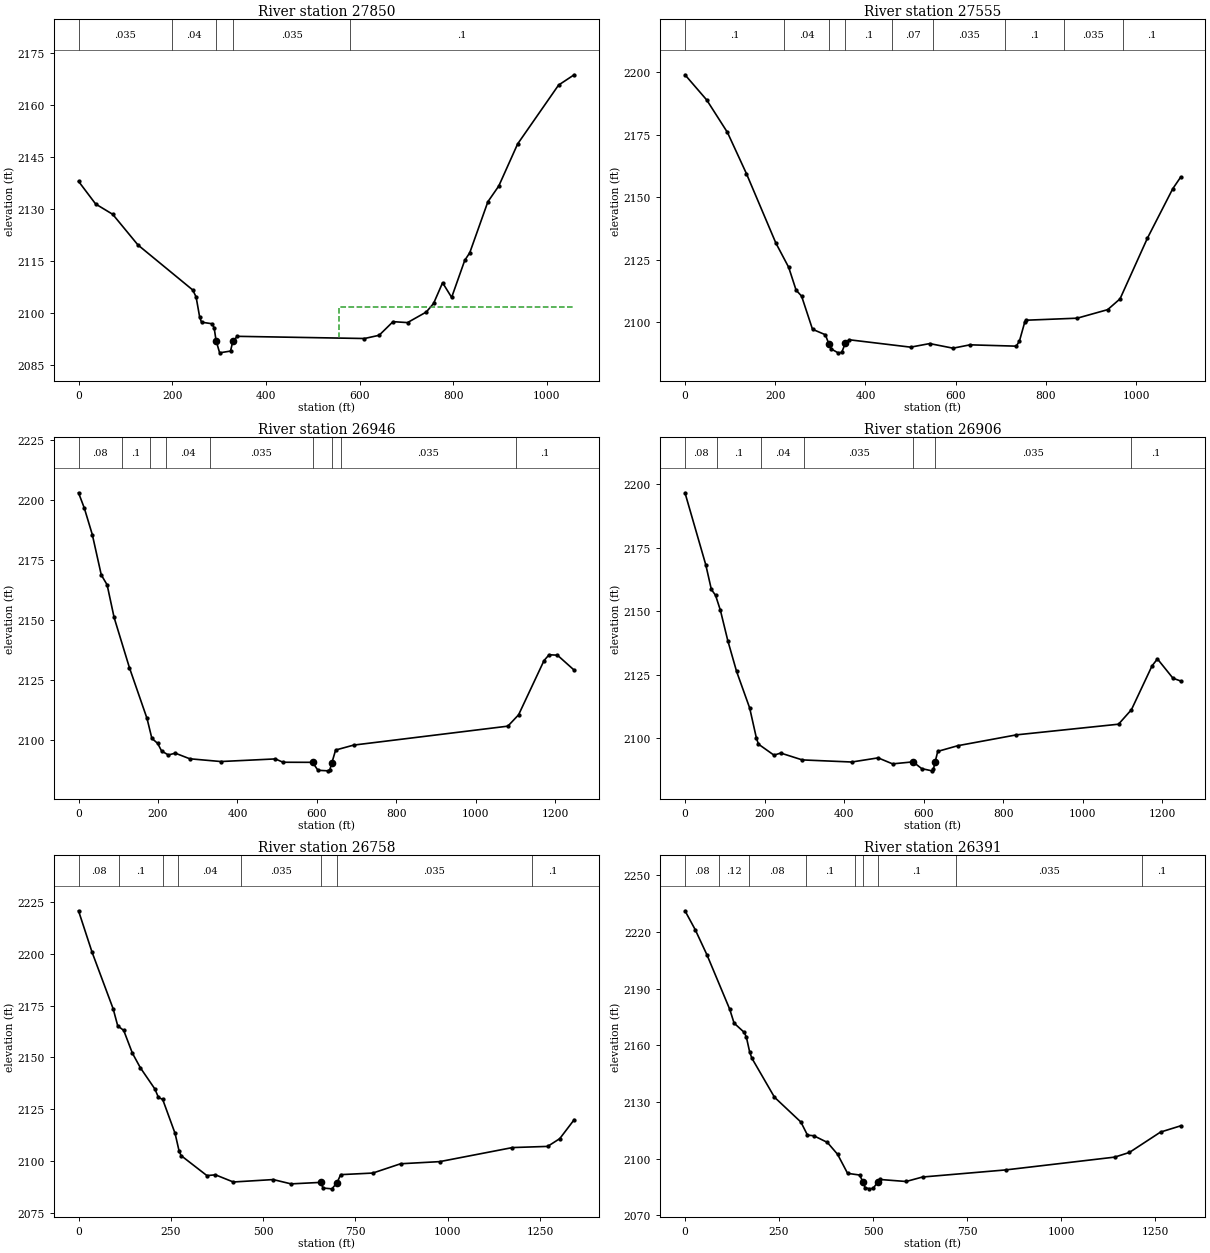
Type RM Length L Ch R = 1 ,27850   ,297.3,295.2,294.4
XS GIS Cut Line= 2
     2147556.126      189184.666     2148453.267      188623.545
#Sta/Elev= 30
       0 2138.07    36.6 2131.52      73 2128.55     127  2119.7   243.8 2106.74
     251 2104.75   258.7 2098.89   262.6 2097.45   285.8 2096.98   289.7 2095.71
   293.7 2092.14   301.3 2088.61   324.5 2089.12   329.5 2091.94     339 2093.37
   610.4 2092.74   641.8 2093.67   671.5  2097.6   702.4 2097.33   742.5 2100.38
     758 2102.84   777.3 2108.82   796.6 2104.59   824.6 2115.28   835.3 2117.47
     874 2132.18   897.2  2136.7   937.5 2148.84  1024.9 2165.81  1058.2 2168.78
#Mann= 5 ,-1 , 0
       0    .035       0     200     .04       0   293.7    .045       0
   329.5    .035       0     580      .1       0
#XS Ineff= 2 , 0
                          555.25         2101.95
Permanent Ineff=
       F       F
Bank Sta=293.7,329.5
XS Rating Curve= 0 ,0
Exp/Cntr=0.3,0.1

Type RM Length L Ch R = 1 ,27555   ,592.3,608.8,615.5
XS GIS Cut Line= 4
2147635.62845574189480.4847646122147798.09064759189383.698777978
2148171.40802461189114.080672356 2148513.6156202188823.722712455
#Sta/Elev= 30
       0 2198.99    48.2 2188.92    94.1 2175.96   136.1 2159.52   201.4 2131.74
   229.8 2122.05   246.2 2112.94   258.4 2110.53   282.6 2097.28     311  2095.1
   319.1 2091.34   323.8 2089.44   339.3 2087.86   347.3 2088.03   355.5 2091.77
   363.7 2093.09     500 2090.13   542.3 2091.56     594 2089.72   631.6 2091.06
   734.2 2090.53   741.2 2092.58   752.8 2100.05   756.2  2100.9   869.2 2101.71
   936.7 2105.12   964.1 2109.43  1024.9 2133.73    1081 2153.46  1098.4 2158.07
#Mann= 9 ,-1 , 0
       0      .1       0  219.11     .04       0   319.1    .045       0
   355.5      .1       0  459.11     .07       0  549.11    .035       0
  709.61      .1       0  839.61    .035       0  969.61      .1       0
Bank Sta=319.1,355.5
XS Rating Curve= 0 ,0
Exp/Cntr(USF)=0,0
Exp/Cntr=0.5,0.3

Type RM Length L Ch R = 1 ,26946   ,39.9,40.1,40.1
XS GIS Cut Line= 3
     2147819.889      189648.695     2148501.742      189309.673
      2148614.38      188836.911
#Sta/Elev= 30
       0  2202.9    14.5 2196.56    34.7 2185.48    57.3 2168.65      72 2164.52
    89.6 2150.91   128.3  2129.9   172.4 2108.82   184.6 2100.52   199.3  2098.4
   209.1 2095.24   226.2 2093.58   243.5 2094.34     280    2092   358.3 2090.85
   495.4 2091.94   514.7 2090.55     5892090.517   602.6  2087.2   628.3 2086.97
   632.4 2087.35   637.3 2090.12   647.1 2095.64   692.4  2097.7  1080.6  2105.6
  1107.6 2110.33  1171.7 2132.96  1184.4 2135.37  1205.4 2135.19  1247.5 2128.95
#Mann= 9 ,-1 , 0
       0     .08       0     110      .1       0     180     .07       0
     220     .04       0     330    .035       0     589    .045       0
   637.3     .08       0     660    .035       0 1101.49      .1       0
#XS Ineff= 2 , 0
          577.65 2089.72  643.84         2090.02
Permanent Ineff=
       F       F
Bank Sta=589,637.3
XS Rating Curve= 0 ,0
Exp/Cntr=0.5,0.3

Type RM Length L Ch R = 1 ,26906   ,153,147.8,143.8
XS GIS Cut Line= 3
     2147849.726      189678.318     2148512.593      189348.736
     2148629.703      188857.204
#Sta/Elev= 30
       0 2196.54    52.3  2168.2    66.3 2158.53    76.8 2156.23      89 2150.33
   107.6  2138.4   129.6 2126.33   162.6  2111.9   179.5 2100.07   184.6  2097.7
   223.6 2093.37   240.7 2094.19   294.7  2091.5   419.1 2090.67   485.4  2092.3
   521.7 2089.94   573.22090.732   594.9 2088.07   620.6  2087.2   624.2 2087.75
   628.42090.557   635.2 2094.85   686.1  2097.1   833.1 2101.35  1089.5 2105.54
    1122 2111.25  1173.8 2128.49  1187.3 2131.21  1226.3 2123.63  1245.6 2122.53
#Mann= 7 ,-1 , 0
       0     .08       0      80      .1       0     190     .04       0
     300    .035       0   573.2    .045       0   628.4    .035       0
 1120.28      .1       0
#XS Ineff= 2 , 0
          565.62 2089.89  639.83         2089.89
Permanent Ineff=
       F       F
Bank Sta=573.2,628.4
XS Rating Curve= 0 ,0
Exp/Cntr=0.5,0.3

Type RM Length L Ch R = 1 ,26758   ,360.3,366.8,351.9
XS GIS Cut Line= 4
2147929.74025234189928.3355790532148377.13338864189595.986392086
2148650.68233484 189411.91607315 2148637.8996738188956.853340226
#Sta/Elev= 30
       0 2220.72    36.7 2200.75    93.9 2173.42   106.2 2165.25   122.4 2163.04
   145.8 2152.12   167.5 2145.03   206.8 2134.81   216.5 2130.71   227.9 2129.79
   261.5 2113.39   272.4 2104.88   277.9 2102.67   347.7 2093.05   370.9 2093.41
   419.2 2089.96   527.2 2091.13   575.6 2089.05   655.5 2089.77   662.5 2087.04
   686.2 2086.66   700.12089.575   709.8  2093.5     797 2094.27   872.2 2098.75
   978.3 2099.78  1175.2 2106.56  1270.4 2107.12  1303.2 2110.85  1342.3 2119.99
#Mann= 8 ,-1 , 0
       0     .08       0     110      .1       0     230     .05       0
     270     .04       0     440    .035       0   655.5    .045       0
   700.1    .035       0 1227.04      .1       0
Bank Sta=655.5,700.1
XS Rating Curve= 0 ,0
Exp/Cntr(USF)=0,0
Exp/Cntr=0.3,0.1

Type RM Length L Ch R = 1 ,26391   ,261.7,250.9,229.1
XS GIS Cut Line= 6
2148152.15855439190173.7626709672148384.80298526189966.683562165
 2148706.9260434189626.6647785752148772.44694717189531.951523793
2148796.60065442189444.3943350092149018.51283979189196.818835689
#Sta/Elev= 30
       0 2231.23    27.2 2221.24    58.5 2207.88     119  2179.1   130.6 2171.74
   157.9 2166.79   163.4 2164.22   172.1 2156.44   177.7 2153.25     238 2132.52
   308.3 2119.36   325.8 2112.44   342.6 2112.11   378.7 2108.58   405.8 2102.31
   432.5  2092.2   464.6 2091.31  472.93 2087.82   478.9 2084.68   490.5    2084
   500.7 2084.26   512.62087.638   518.8 2088.95     588 2087.89   631.8 2090.26
   852.6 2094.01  1143.1  2100.8    1182 2103.27  1264.8 2114.05  1318.3 2117.36
#Mann= 9 ,-1 , 0
       0     .08       0      90     .12       0     170     .08       0
  321.46      .1       0  451.46     .04       0  472.93    .045       0
   512.6      .1       0  721.46    .035       0 1215.83      .1       0
Bank Sta=472.93,512.6
XS Rating Curve= 0 ,0
Exp/Cntr(USF)=0,0
Exp/Cntr=0.5,0.3

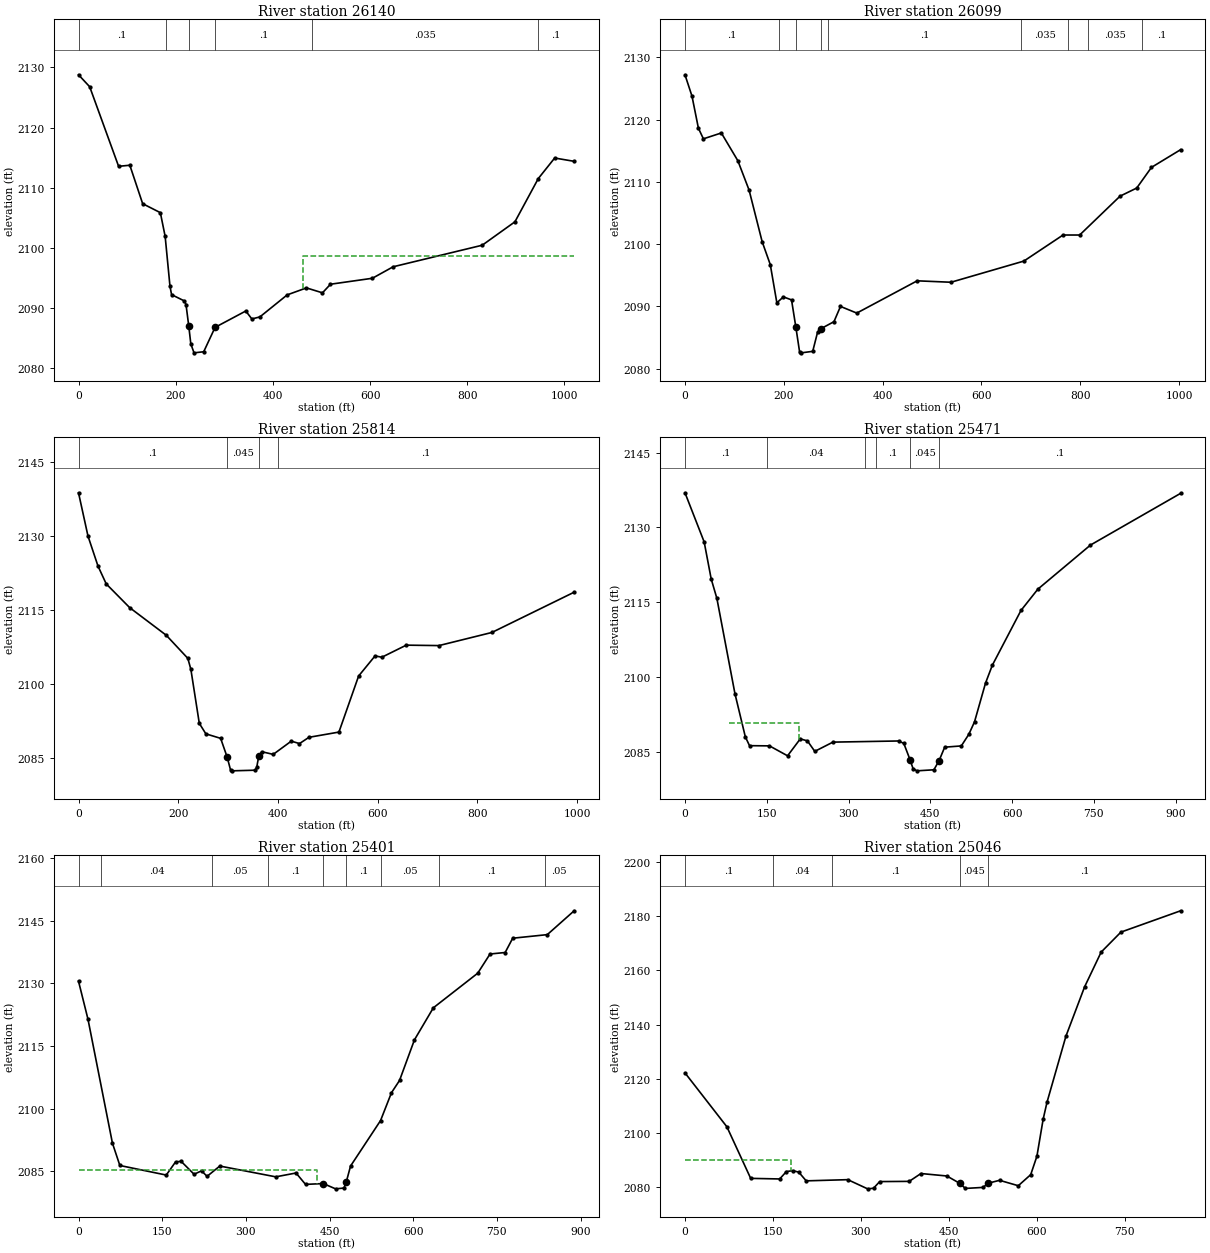
Type RM Length L Ch R = 1 ,26140   ,41.5,41.5,41.9
XS GIS Cut Line= 3
     2148718.756      190140.837     2148799.051      189459.413
     2149026.586      189215.254
#Sta/Elev= 30
       0 2128.77      23 2126.78    82.5 2113.56   105.6 2113.74     132 2107.35
   168.4 2105.86   178.3 2101.91   188.2 2093.64   191.5 2092.24   217.9 2091.19
   221.2  2090.6  226.962086.958   231.1 2084.05   237.7 2082.57   257.6 2082.75
     2812086.801   344.2 2089.52   356.7  2088.2   373.2 2088.54   429.4  2092.2
     469 2093.36     502 2092.54   518.5 2093.97   604.7 2094.96   647.4 2096.87
   830.7 2100.45     898 2104.34   946.1 2111.53   979.8 2114.94  1019.9 2114.39
#Mann= 6 ,-1 , 0
       0      .1       0     180     .04       0  226.96    .045       0
     281      .1       0     480    .035       0  946.14      .1       0
#XS Ineff= 2 , 0
             220 2086.15  462.46         2098.66
Permanent Ineff=
       F       F
Bank Sta=226.96,281
XS Rating Curve= 0 ,0
Exp/Cntr=0.5,0.3

Type RM Length L Ch R = 1 ,26099   ,285.4,284.8,283.7
XS GIS Cut Line= 3
     2148759.988      190145.177     2148840.284      189463.753
     2149056.605      189231.628
#Sta/Elev= 30
       0 2127.19    14.2 2123.76    27.2 2118.61    37.3 2116.91    73.6 2117.85
     107  2113.4   129.8 2108.68   156.2 2100.41   172.7 2096.72     186 2090.59
   199.2 2091.54   215.7 2091.06  224.522086.655   232.2 2082.62   235.5 2082.56
   258.6  2082.8   268.5  2085.9   274.52086.406   301.6 2087.56   314.8 2090.01
   347.8 2088.94   470.1 2094.12   538.5 2093.89   686.1 2097.29   765.3 2101.47
     799 2101.47   880.8 2107.71   914.5 2109.01   944.4 2112.33  1003.4 2115.17
#Mann= 9 ,-1 , 0
       0      .1       0     190     .04       0  224.52    .045       0
   274.5     .04       0     290      .1       0     680    .035       0
  776.14      .1       0  816.14    .035       0  926.14      .1       0
#XS Ineff= 2 , 0
             221 2086.15     277         2086.15
Permanent Ineff=
       F       F
Bank Sta=224.52,274.5
XS Rating Curve= 0 ,0
Exp/Cntr=0.5,0.3

Type RM Length L Ch R = 1 ,25814   ,354.4,343.3,330.1
XS GIS Cut Line= 4
2149021.74205003 190254.772657682149059.76511621190057.744042033
2149101.24482476189608.3805326632149170.37767236189273.086221825
#Sta/Elev= 30
       0 2138.73      19 2129.95    39.1 2123.86    55.6 2120.25   102.6 2115.44
   176.1 2109.83   219.3 2105.15   225.4 2102.92   242.3 2091.97   255.5 2089.84
   285.1 2088.93   298.3 2085.09   304.9 2082.55   308.2 2082.34   354.3 2082.47
   357.6  2083.1   361.52085.298   367.5 2086.22   390.6 2085.68   426.8 2088.36
   443.3 2087.87   462.3 2089.14   522.4  2090.2   561.9 2101.57   594.9 2105.65
   608.5 2105.38   657.5 2107.83     723 2107.74   829.2  2110.4   994.3 2118.57
#Mann= 4 ,-1 , 0
       0      .1       0   298.3    .045       0   361.5     .04       0
  400.66      .1       0
Bank Sta=298.3,361.5
XS Rating Curve= 0 ,0
Exp/Cntr(USF)=0,0
Exp/Cntr=0.5,0.3

Type RM Length L Ch R = 1 ,25471   ,68.6,69.4,69.3
XS GIS Cut Line= 4
     2149339.416      190303.597      2149404.52      189917.312
     2149350.266       189724.17     2149446.297      189422.218
#Sta/Elev= 30
       0 2136.94    35.2  2127.1    48.1 2119.68    58.5  2115.8    91.7 2096.69
   110.7 2088.07   118.4  2086.3     155 2086.26   188.2 2084.27   211.5 2087.66
   224.6 2087.26   238.1 2085.16   271.4 2087.01   391.7 2087.24   401.4 2086.76
  412.862083.478   418.4 2081.69   425.3 2081.26   456.6 2081.47   466.22083.325
   476.4    2086   506.9 2086.25   520.7 2088.58   531.1 2091.07   551.3 2098.83
   563.8 2102.41   616.3 2113.37   647.3 2117.64   743.8 2126.47   909.2 2136.83
#Mann= 6 ,-1 , 0
       0      .1       0     150     .04       0     330     .05       0
     350      .1       0  412.86    .045       0   466.2      .1       0
#XS Ineff= 3 ,-1
   81.66  209.17 2090.83  224.93  388.252085.084  478.51  912.062085.337
Permanent Ineff=
       F       F       F
Bank Sta=412.86,466.2
XS Rating Curve= 0 ,0
Exp/Cntr=0.5,0.3

Type RM Length L Ch R = 1 ,25401   ,344.3,355.7,372.5
XS GIS Cut Line= 4
 2149403.8066062190296.051564505 2149468.9116062189909.766564505
2149428.52394761189730.490905916 2149506.6706062189427.306564505
#Sta/Elev= 30
       02130.478  16.9832121.372  60.8082091.707  74.1172086.356 157.2942084.063
  173.932087.203 183.9112087.355 207.2012084.255 220.5092085.075 230.4912083.758
 253.3032086.221 353.5942083.639  389.972084.556  406.99 2081.83 438.8482082.028
 460.7992080.765 475.9762080.954 480.2062082.498 487.7042086.222 541.5132097.117
 561.0632103.779 575.5022106.707 602.2452116.437 636.1262124.107 715.7042132.395
 737.768 2136.99 764.872 2137.35 778.4242140.771 840.4192141.628 888.595 2147.34
#Mann= 9 ,-1 , 0
       0      .1       0      40     .04       0     240     .05       0
     340      .1       0 438.848    .045       0 480.206      .1       0
  541.73     .05       0   645.5      .1       0   835.5     .05       0
#XS Ineff= 2 , 0
          428.37 2085.16   495.7         2086.23
Permanent Ineff=
       F       F
Bank Sta=438.848,480.206
XS Rating Curve= 0 ,0
Exp/Cntr=0.5,0.3

Type RM Length L Ch R = 1 ,25046   ,494.2,500,498.9
XS GIS Cut Line= 3
     2149670.131      190403.948     2149787.839      189930.341
     2149921.394       189598.52
#Sta/Elev= 30
       0 2122.15    71.5 2102.23   112.1 2083.17   161.6 2082.95     173 2085.68
   183.8 2086.02   194.1 2085.48   206.8 2082.25   277.8 2082.69   311.6  2079.3
   321.7 2079.52   332.2 2081.98   382.6 2082.06   402.6 2084.96   446.8 2084.05
   468.42081.385   478.4 2079.45   508.6 2079.83   517.3 2081.38   536.8 2082.45
   568.7 2080.45   589.9 2084.54   600.5 2091.37   611.1    2105   617.7  2111.3
     650 2135.72   681.8 2153.92   710.1 2166.78   743.8 2174.16   845.7 2182.05
#Mann= 5 ,-1 , 0
       0      .1       0     150     .04       0     250      .1       0
   468.4    .045       0   517.3      .1       0
#XS Ineff= 2 , 0
          181.63 2090.03
Permanent Ineff=
       F       F
Bank Sta=468.4,517.3
XS Rating Curve= 0 ,0
Exp/Cntr=0.3,0.1

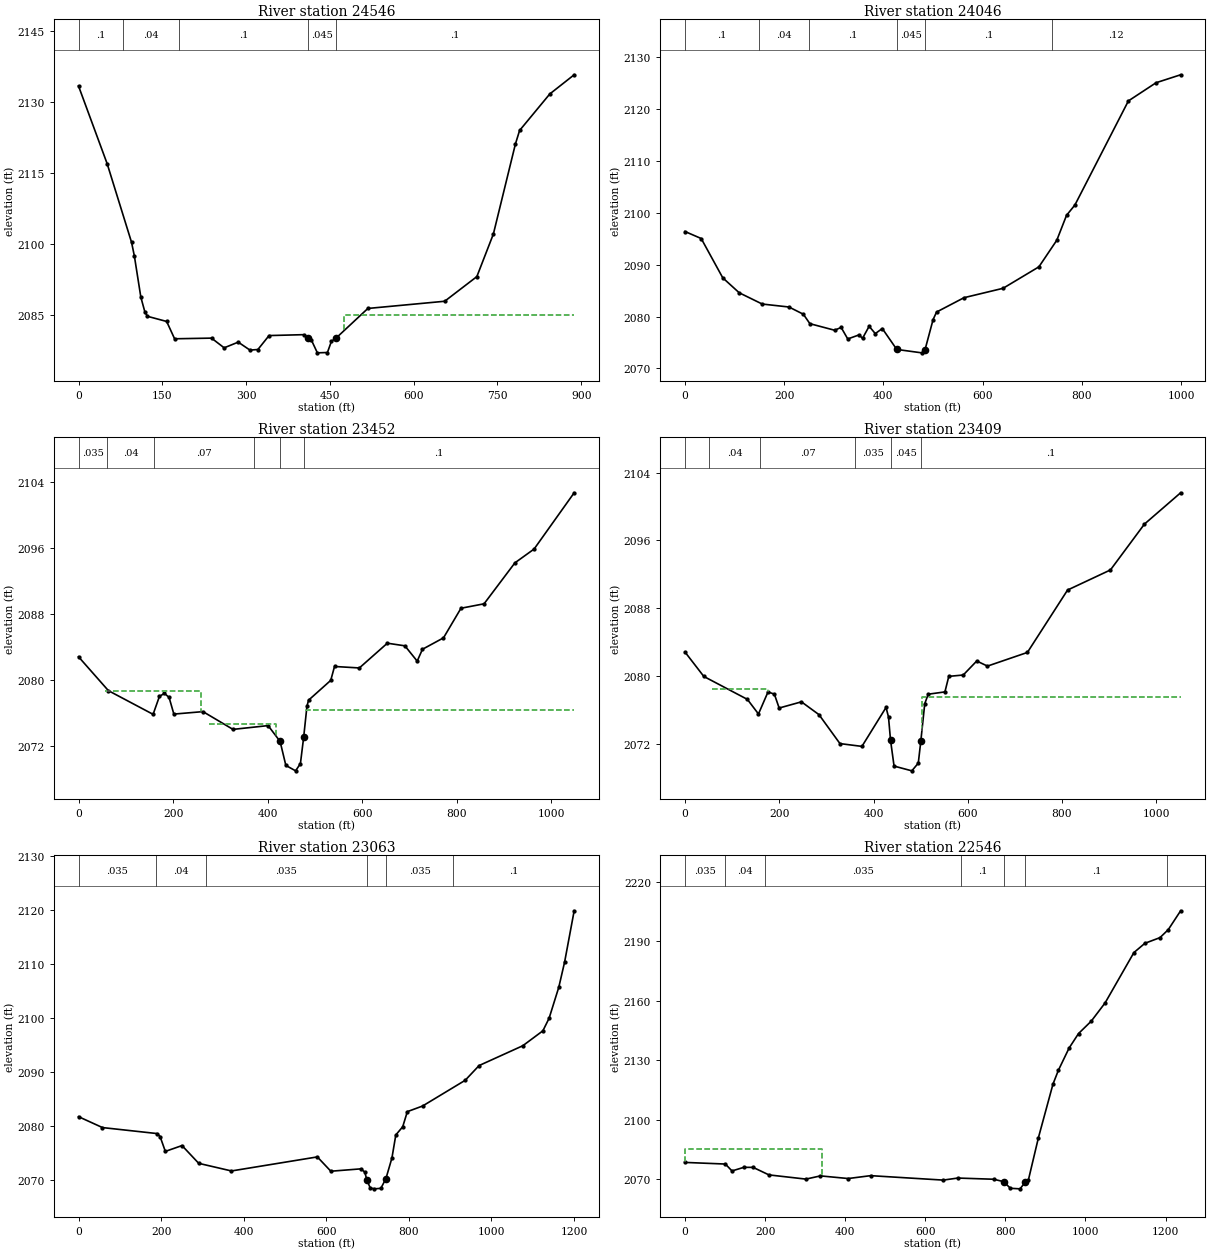
Type RM Length L Ch R = 1 ,24546   ,521.7,500,489.1
XS GIS Cut Line= 3
      2150064.25      190522.964      2150231.04      190119.887
     2150421.614      189711.096
#Sta/Elev= 30
       0 2133.42    51.3 2116.99      95 2100.36     100 2097.49   111.6 2088.78
   118.7 2085.72   123.4 2084.75   157.8 2083.66     172    2080   238.1 2080.14
   260.7 2078.09   285.9 2079.29   306.9 2077.61   321.1 2077.73   341.1 2080.68
   402.8 2080.87   411.62080.224     417  2079.7   427.6 2077.03   445.6  2077.1
   452.8 2079.48   460.92080.132     518 2086.41   655.5 2087.93   713.1 2093.14
   742.7 2102.15   782.1 2121.15   789.6 2124.02   843.7 2131.74   887.3 2135.79
#Mann= 5 ,-1 , 0
       0      .1       0      80     .04       0     180      .1       0
   411.6    .045       0   460.9      .1       0
#XS Ineff= 1 ,-1
  475.75   887.2 2085.02
Permanent Ineff=
       F
Bank Sta=411.6,460.9
XS Rating Curve= 0 ,0
Exp/Cntr=0.3,0.1

Type RM Length L Ch R = 1 ,24046   ,580.6,593.3,605.3
XS GIS Cut Line= 3
     2150781.636      190695.381     2150715.273      190230.831
     2150719.752      189700.971
#Sta/Elev= 30
       0 2096.36    32.7 2095.01    76.2 2087.44   109.3 2084.57   155.7  2082.4
   209.6 2081.83   238.6 2080.44   251.8 2078.62   301.6 2077.36   314.8  2077.9
   328.1 2075.68   350.8 2076.46   357.9  2075.8   371.2 2078.12   383.6 2076.71
   397.7 2077.69   426.92073.665   477.1 2073.01  483.872073.604   500.1  2079.4
   507.1 2080.86   562.4 2083.62   641.2 2085.43   713.4 2089.56   749.5 2094.68
   769.1 2099.47     786 2101.46   893.8 2121.49   949.6 2124.99   999.1 2126.52
#Mann= 6 ,-1 , 0
       0      .1       0     150     .04       0     250      .1       0
   426.9    .045       0  483.87      .1       0  739.27     .12       0
Bank Sta=426.9,483.87
XS Rating Curve= 0 ,0
Exp/Cntr=0.5,0.3

Type RM Length L Ch R = 1 ,23452   ,40.8,43.6,52.5
XS GIS Cut Line= 4
     2151368.846      190513.986     2151270.839      190112.625
     2151305.561      189997.607     2151066.111      189541.986
#Sta/Elev= 30
       0 2082.79    63.2 2078.67   157.7 2075.79   171.2 2077.99   181.8 2078.33
   191.5 2077.85   201.6 2075.82   263.2 2076.12   326.6 2073.96   400.9 2074.42
   426.2  2072.5   438.4 2069.58     459 2068.92   469.2  2069.8     4762072.978
     483 2076.77   486.4 2077.51   533.3 2079.92   541.3 2081.61   593.8 2081.43
     653 2084.44   690.1 2084.12   716.1 2082.26   727.2  2083.7   771.7 2085.09
   808.7 2088.69   857.5 2089.23   922.7 2094.21   963.3 2095.89    1048 2102.73
#Mann= 6 ,-1 , 0
       0    .035       0      60     .04       0     160     .07       0
     370    .035       0   426.2    .045       0     476      .1       0
#XS Ineff= 3 ,-1
   56.73   259.6 2078.57  276.79  417.77 2074.57     482    1048 2076.26
Permanent Ineff=
       F       F       F
Bank Sta=426.2,476
XS Rating Curve= 0 ,0
Exp/Cntr=0.5,0.3

Type RM Length L Ch R = 1 ,23409   ,371.5,345.7,308.2
XS GIS Cut Line= 4
     2151396.135      190505.661     2151301.221      190116.965
     2151335.943      190001.948     2151088.751      189531.595
#Sta/Elev= 30
       0 2082.86      40 2079.98   132.4 2077.28   155.9 2075.56   176.2 2078.16
   189.7 2077.89   199.8 2076.26   247.1 2076.99   284.3 2075.48   328.8 2072.07
   375.4 2071.74   426.6 2076.33   431.8  2075.2   436.1 2072.47   443.6 2069.42
   481.3 2068.86     495 2069.77   500.3 2072.33   508.7 2076.77   516.1 2077.89
   551.5 2078.16   559.7 2079.99   590.4 2080.15     619  2081.8   641.8  2081.2
   726.5 2082.81   811.7 2090.16   902.7 2092.53   974.8 2097.93  1051.6 2101.62
#Mann= 6 ,-1 , 0
       0    .035       0      50     .04       0     160     .07       0
     360    .035       0   436.1    .045       0   500.3      .1       0
#XS Ineff= 3 ,-1
   56.73  177.08 2078.54  251.88  422.682074.779  502.59 1057.192077.607
Permanent Ineff=
       F       F       F
Bank Sta=436.1,500.3
XS Rating Curve= 0 ,0
Exp/Cntr=0.5,0.3

Type RM Length L Ch R = 1 ,23063   ,498.8,517.4,526
XS GIS Cut Line= 3
      2151882.58      190421.946     2151922.579      190310.839
     2151288.965      189433.167
#Sta/Elev= 30
       0 2081.66    58.1 2079.64   190.5 2078.53   197.6 2077.98   210.3 2075.23
   250.7 2076.31   291.2 2073.02   370.5 2071.61   578.5 2074.21   611.2 2071.56
     684    2072   693.4  2071.4   698.72069.887   706.8 2068.44   716.9  2068.3
   732.3 2068.39   744.62070.185   759.2 2074.02   768.6 2078.28   785.3 2079.79
   796.5 2082.59   833.4 2083.63   936.6 2088.39   970.3 2091.12  1076.2 2094.79
  1124.8 2097.55  1139.9 2099.88  1163.4 2105.63  1177.4 2110.26  1200.6 2119.77
#Mann= 6 ,-1 , 0
       0    .035       0  188.09     .04       0  308.09    .035       0
   698.7    .045       0   744.6    .035       0  908.09      .1       0
Bank Sta=698.7,744.6
XS Rating Curve= 0 ,0
Exp/Cntr=0.3,0.1

Type RM Length L Ch R = 1 ,22546   ,482.6,500,518.3
XS GIS Cut Line= 3
     2152076.436      190356.126     2151993.054      189535.513
     2151874.294      189140.106
#Sta/Elev= 30
       0 2078.52   100.9  2077.7   117.4 2074.22     147 2076.04   170.1 2076.02
   209.7 2072.22     302  2070.1   338.3 2071.72   407.6 2070.39   463.6 2071.84
   644.8  2069.6   681.3 2070.63   770.9 2070.03   795.42068.834   812.8 2065.46
   836.7 2065.19   849.92068.609   857.3 2069.45   882.7 2091.08   918.9    2118
   932.6 2125.07   959.1 2136.19   982.8 2143.54  1014.5 2149.78  1049.1 2158.99
    1121 2184.38  1148.4 2189.05  1186.1 2191.91  1206.8 2195.94  1237.7 2205.46
#Mann= 7 ,-1 , 0
       0    .035       0     100     .04       0     200    .035       0
     690      .1       0   795.4    .045       0   849.9      .1       0
 1204.84    .035       0
#XS Ineff= 2 , 0
          342.98 2085.34
Permanent Ineff=
       F       F
Bank Sta=795.4,849.9
XS Rating Curve= 0 ,0
Exp/Cntr=0.3,0.1

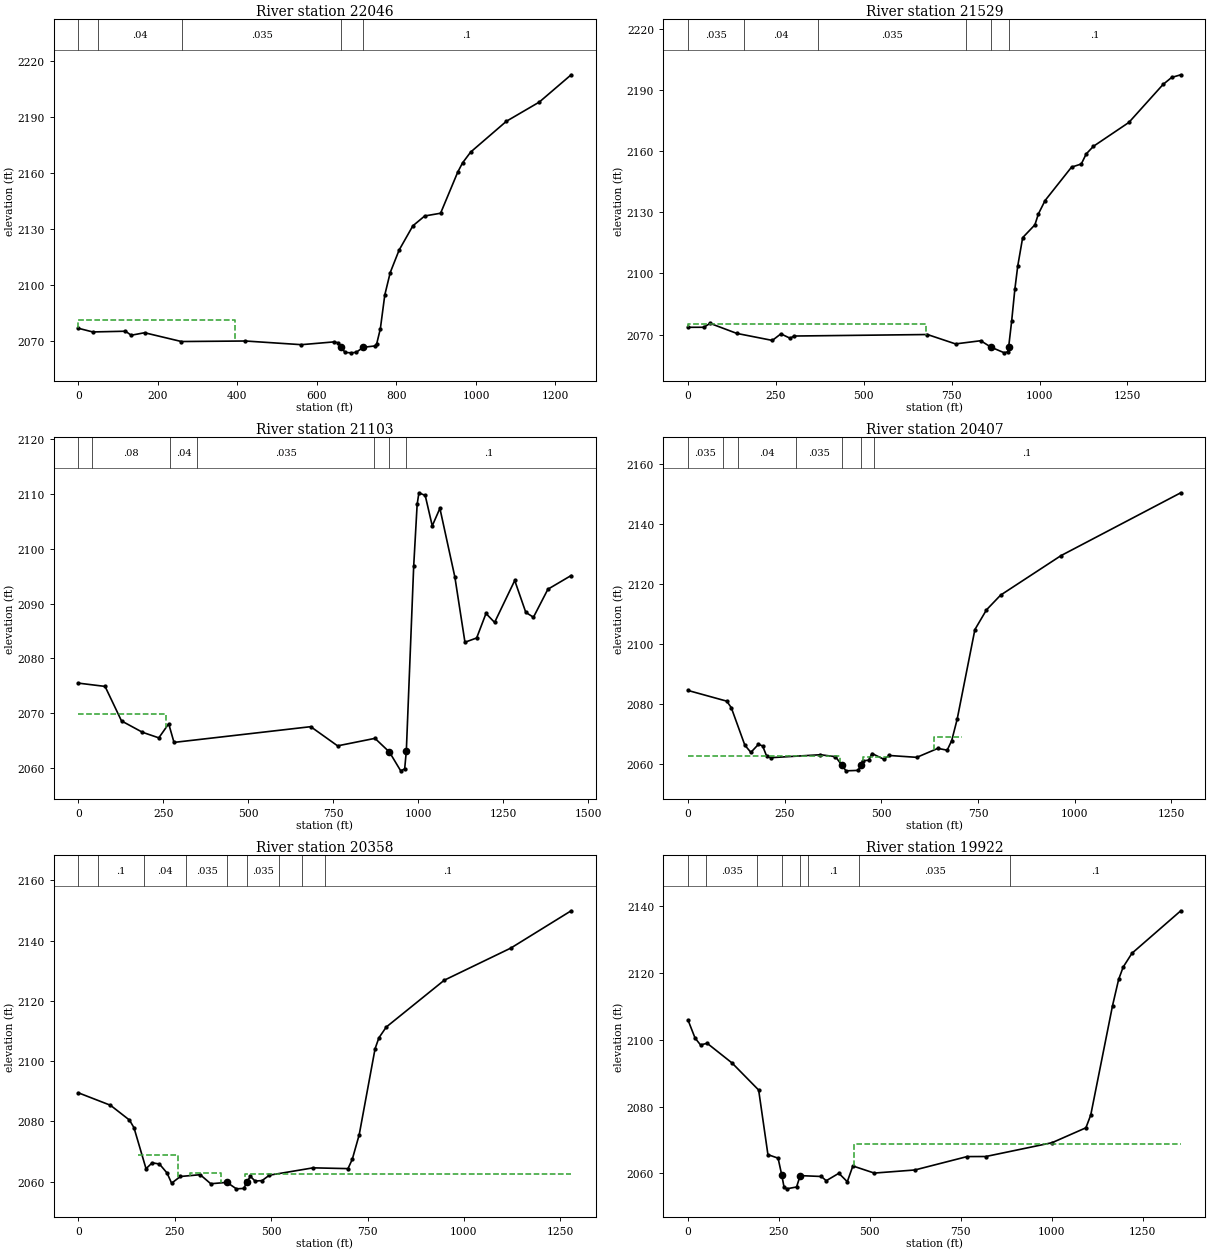
Type RM Length L Ch R = 1 ,22046   ,512.9,516.9,509.9
XS GIS Cut Line= 3
     2152234.265      190401.972     2152431.793       189750.81
     2152661.234      189241.117
#Sta/Elev= 30
       0  2076.8    36.2 2074.83   118.5 2075.22   132.9 2073.06   166.5 2074.41
   259.2 2069.69   420.2 2069.97   560.8    2068   643.2  2069.5   653.3 2068.99
  661.612066.586   670.5 2063.83   686.5 2063.62   698.8  2063.9   716.42066.595
   745.5 2067.31   750.4 2068.54   759.5 2076.56   770.7 2094.71   784.3 2106.67
   806.7 2118.78   841.3 2131.79   871.1 2137.07     911 2138.54   954.2 2160.64
   966.2 2165.54   986.6 2171.36  1076.5 2187.89  1159.3  2198.2  1239.4 2212.84
#Mann= 5 ,-1 , 0
       0    .035       0      50     .04       0     260    .035       0
  661.61    .045       0   716.4      .1       0
#XS Ineff= 2 , 0
          395.13 2081.17
Permanent Ineff=
       F       F
Bank Sta=661.61,716.4
XS Rating Curve= 0 ,0
Exp/Cntr=0.3,0.1

Type RM Length L Ch R = 1 ,21529   ,425.6,425.2,424.2
XS GIS Cut Line= 2
     2152641.736      190702.266     2153102.475      189378.201
#Sta/Elev= 30
       0 2073.59    45.5 2073.61    62.8 2075.53   138.8  2070.6     240 2067.16
   264.3 2070.38   290.8  2068.2   301.1 2069.31   681.2 2070.05   761.1 2065.45
   832.9 2067.01   861.52063.894     900 2061.07   909.3 2061.61   912.32063.996
   920.9 2076.79   929.9 2092.29   938.2 2103.75   952.1 2117.55   986.9 2123.84
   996.9  2129.2  1015.9 2135.76  1091.1 2152.12  1118.9 2153.67  1132.8 2158.58
  1153.6 2162.36  1254.4 2174.06  1351.6 2192.68  1375.9  2196.1  1401.9 2197.41
#Mann= 6 ,-1 , 0
       0    .035       0     160     .04       0     370    .035       0
     790      .1       0   861.5    .045       0   912.3      .1       0
#XS Ineff= 2 , 0
          676.22  2075.1
Permanent Ineff=
       F       F
Bank Sta=861.5,912.3
XS Rating Curve= 0 ,0
Exp/Cntr=0.3,0.1

Type RM Length L Ch R = 1 ,21103   ,672.3,696.9,689.8
XS GIS Cut Line= 2
     2153055.608      190885.139     2153487.691      189501.553
#Sta/Elev= 30
       0 2075.49    78.5 2074.89   126.9 2068.59   188.5 2066.52   236.6  2065.5
   265.7 2068.07   281.3 2064.67   683.4 2067.54   762.5 2064.04   872.4 2065.41
     9152062.905   948.1 2059.48   959.8 2059.83  964.682063.137   986.3 2096.82
   996.5 2108.13  1001.7 2110.23  1020.2 2109.74  1040.9 2104.19  1063.4 2107.39
  1107.4 2094.86  1137.1 2082.95  1171.5 2083.73    1199  2088.2  1224.3 2086.57
  1283.5 2094.22    1316 2088.41  1338.5 2087.51  1381.1 2092.63  1449.5 2095.13
#Mann= 7 ,-1 , 0
       0      .1       0      40     .08       0     270     .04       0
     350    .035       0     870      .1       0     915    .045       0
  964.68      .1       0
#XS Ineff= 2 , 0
          257.59 2069.86
Permanent Ineff=
       F       F
Bank Sta=915,964.68
XS Rating Curve= 0 ,0
Exp/Cntr=0.5,0.3

Type RM Length L Ch R = 1 ,20407   ,48.9,48.3,47.8
XS GIS Cut Line= 3
     2153380.214      190956.809     2153775.179       190344.83
     2153861.103      189805.345
#Sta/Elev= 30
       0 2084.37   100.3  2080.8     112 2078.63   147.1 2066.11   162.7 2063.73
   182.3 2066.41   193.1 2065.86   203.8 2062.37   215.9 2061.97   342.6 2062.94
   381.4 2062.29   398.52059.395   408.7 2057.57   439.9 2057.72   447.5  2059.4
   451.7 2060.93   467.3  2061.1     476 2063.35   506.4 2061.44   520.6 2062.69
   591.8 2062.07   646.3 2065.06   670.4 2064.45   682.1 2067.64   696.2 2074.76
   742.1 2104.67     772 2111.23   808.6 2116.15   964.7 2129.31  1274.6 2150.27
#Mann= 7 ,-1 , 0
       0    .035       0      90      .1       0     130     .04       0
     280    .035       0   398.5    .045       0   447.5    .035       0
     480      .1       0
#XS Ineff= 3 ,-1
       0     392 2062.41   453.3   525.5 2062.35  635.82  708.02 2068.94
Permanent Ineff=
       F       F       F
Bank Sta=398.5,447.5
XS Rating Curve= 0 ,0
Exp/Cntr=0.5,0.3

Type RM Length L Ch R = 1 ,20358   ,427.2,436,441.3
XS GIS Cut Line= 3
     2153412.766      190987.191     2153807.732      190375.212
     2153894.212      189832.226
#Sta/Elev= 30
       0 2089.49    83.2 2085.36   132.5 2080.45   144.2 2077.92   175.5 2064.31
   191.5 2066.26   210.3 2065.86   230.1 2062.86   241.8  2059.5   264.7 2061.72
     316 2062.31   343.4 2059.31   385.42059.766   409.9 2057.62   429.3 2057.76
  436.522059.808   446.2 2061.77   458.3  2060.2   476.5 2060.35   495.3 2062.15
   608.9 2064.59   699.3 2064.33   710.4  2067.4   728.4 2075.57   769.6 2104.13
   779.5 2107.74   798.6 2111.32     949 2126.86  1121.7 2137.53  1278.2 2149.91
#Mann= 9 ,-1 , 0
       0    .035       0      50      .1       0     170     .04       0
     280    .035       0   385.4    .045       0  436.52    .035       0
     520      .1       0     580    .035       0     640      .1       0
#XS Ineff= 3 ,-1
  154.44  258.74 2068.94  290.83  369.05 2062.82     433  1278.2 2062.41
Permanent Ineff=
       F       F       F
Bank Sta=385.4,436.52
XS Rating Curve= 0 ,0
Exp/Cntr=0.5,0.3

Type RM Length L Ch R = 1 ,19922   ,596.3,595.4,588.9
XS GIS Cut Line= 3
     2153685.613      191174.738     2154302.787      190581.672
     2154217.416      190090.789
#Sta/Elev= 30
       0 2105.95    19.4 2100.55    34.5 2098.47    52.7 2098.97     121 2093.08
   194.2 2084.97   219.7 2065.62   247.6 2064.57  257.57 2059.57   263.8 2056.02
   270.8 2055.38   298.4 2055.93   308.3 2059.34   366.7 2059.08   379.8  2057.8
   414.6 2060.04   437.8 2057.51   453.1 2062.23   511.9  2060.1   623.5 2061.03
   767.1 2065.04   818.4 2065.06  1000.3 2069.19  1093.5 2073.66  1106.8 2077.49
  1166.7 2110.26  1183.4 2118.08  1195.9 2121.79    1220 2125.92  1354.2 2138.65
#Mann= 8 ,-1 , 0
       0      .1       0      50    .035       0     190     .04       0
  257.57    .045       0   308.3     .04       0     330      .1       0
     470    .035       0  885.94      .1       0
#XS Ineff= 2 , 0
                           455.3         2068.85
Permanent Ineff=
       F       F
Bank Sta=257.57,308.3
XS Rating Curve= 0 ,0
Exp/Cntr=0.3,0.1

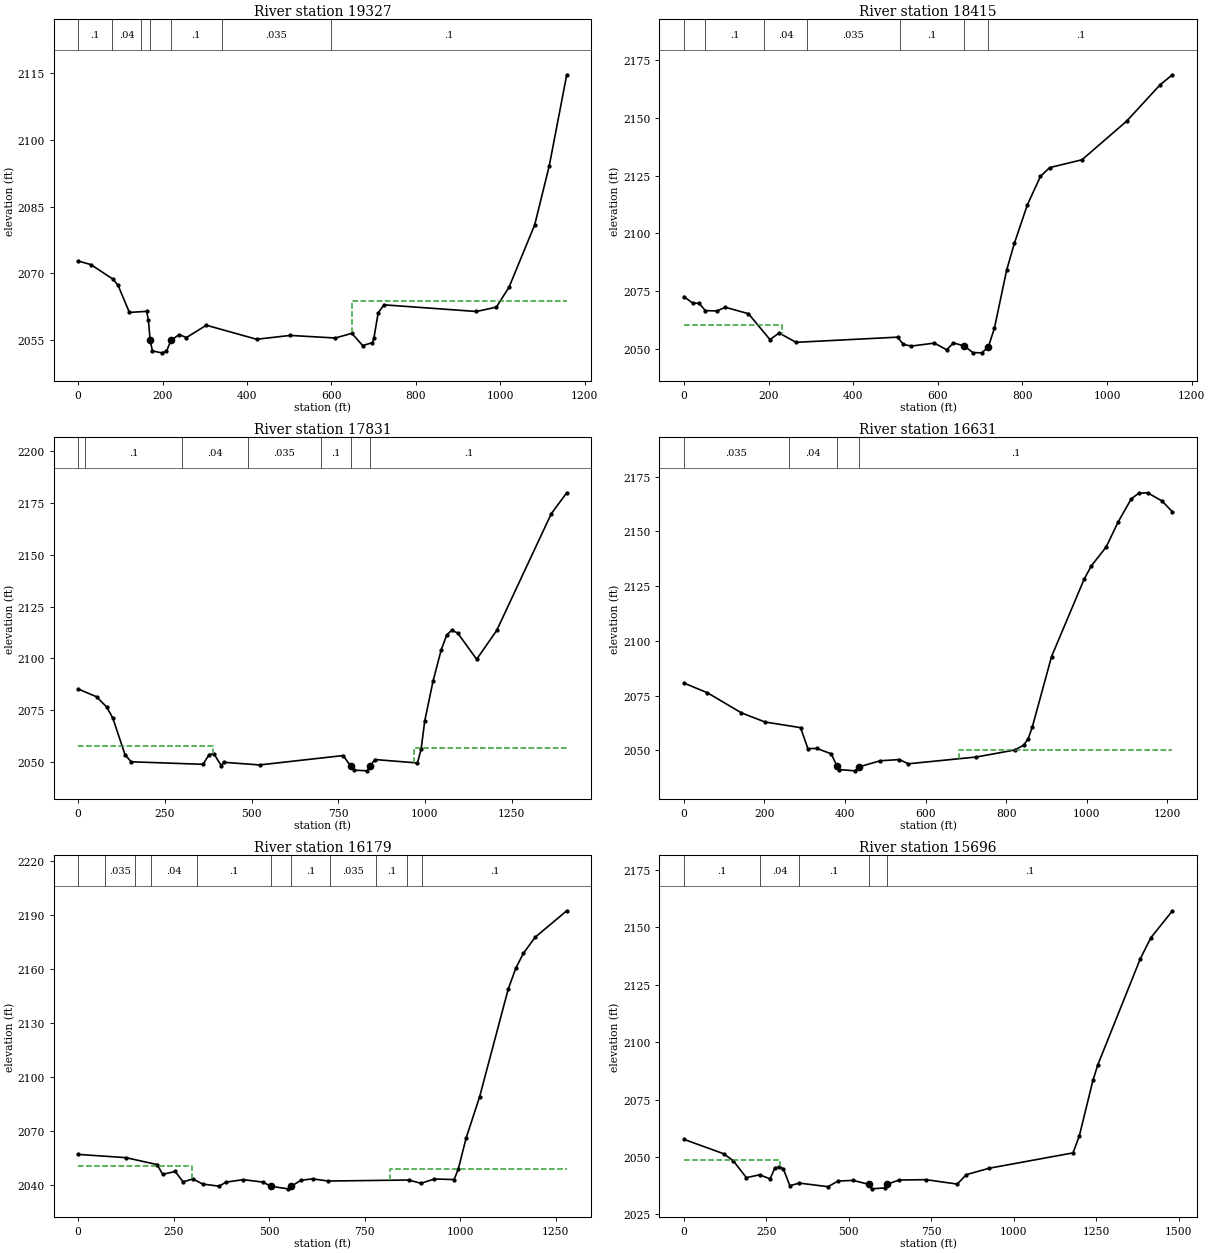
Type RM Length L Ch R = 1 ,19327   ,903.2,912.2,891.8
XS GIS Cut Line= 2
     2154219.454      191498.339     2154966.861      190613.908
#Sta/Elev= 30
       0 2072.77    29.9 2071.98    82.9 2068.67    94.5 2067.32   121.4  2061.2
   162.1 2061.44   166.4 2059.57   170.62054.957     176 2052.53   197.6  2052.1
   209.3 2052.42   219.82054.883   238.9  2056.2   256.6 2055.55   303.8 2058.32
   422.8 2055.16   502.6 2056.02   609.3 2055.44   648.6 2056.49   674.2 2053.74
   697.5  2054.4   700.8 2055.34     711  2061.1   724.8 2062.91   943.9 2061.41
   991.1 2062.39  1021.2 2066.89    1082 2080.92  1116.6 2094.28  1157.9 2114.71
#Mann= 7 ,-1 , 0
       0      .1       0      80     .04       0     150     .06       0
   170.6    .045       0   219.8      .1       0     340    .035       0
     600      .1       0
#XS Ineff= 2 , 0
                          648.92         2063.72
Permanent Ineff=
       F       F
Bank Sta=170.6,219.8
XS Rating Curve= 0 ,0
Exp/Cntr=0.3,0.1

Type RM Length L Ch R = 1 ,18415   ,582.5,583.9,577.5
XS GIS Cut Line= 2
      2154886.12      191899.381     2155381.563      190856.592
#Sta/Elev= 30
       0  2072.7    20.5  2069.9    36.1 2069.76    50.8  2066.6    77.9 2066.48
      98 2068.06   152.5 2065.28   203.3 2054.08   225.1 2056.91     265 2052.88
   504.8 2055.12   518.7 2051.95   537.5 2051.26     592 2052.55     621 2049.64
   636.9 2052.64   662.52051.305   682.8 2048.44   703.4 2048.33   719.1 2050.72
   733.6 2058.87   762.7 2084.13   780.8 2095.68   811.7 2112.45   842.6 2124.74
   864.4 2128.53   940.7 2131.92    1046 2148.61  1125.9  2164.5  1154.5 2168.72
#Mann= 7 ,-1 , 0
       0    .035       0      50      .1       0     190     .04       0
     290    .035       0     510      .1       0   662.5    .045       0
   719.1      .1       0
#XS Ineff= 2 , 0
          232.56  2060.4
Permanent Ineff=
       F       F
Bank Sta=662.5,719.1
XS Rating Curve= 0 ,0
Exp/Cntr=0.3,0.1

Type RM Length L Ch R = 1 ,17831   ,1187.9,1200.1,1188.5
XS GIS Cut Line= 3
     2155391.329      192284.797     2155802.787      191211.881
     2155677.177      190984.425
#Sta/Elev= 30
       0 2085.14    53.7 2081.32    82.4 2076.38     100 2071.03   135.1 2053.39
   152.7 2049.93     360 2048.71   377.6 2053.39   391.1 2053.88   412.7 2048.04
   419.7 2049.68     523 2048.41   764.1 2052.94   785.72047.931   795.7 2045.88
   833.4 2045.55   841.4 2047.71   855.4 2051.02   978.4 2049.36     989 2056.07
   999.5 2069.77  1023.3 2088.89  1046.7 2103.93  1062.7 2111.18  1076.8 2113.55
  1094.4 2112.21  1149.1  2099.5  1206.9 2113.43  1364.4 2169.95  1408.9 2180.03
#Mann= 7 ,-1 , 0
       0     .12       0      20      .1       0     300     .04       0
     490    .035       0     700      .1       0   785.7    .045       0
   841.4      .1       0
#XS Ineff= 2 , 0
          389.68 2057.57   967.6         2056.76
Permanent Ineff=
       F       F
Bank Sta=785.7,841.4
XS Rating Curve= 0 ,0
Exp/Cntr=0.3,0.1

Type RM Length L Ch R = 1 ,16631   ,443.5,451.8,450.9
XS GIS Cut Line= 2
     2156094.454      192555.631     2156634.982      191470.108
#Sta/Elev= 30
       0 2080.75    58.6 2076.29   142.9 2067.12   201.5 2062.97   289.5  2060.4
   307.9 2050.81   329.8 2050.91   365.5 2048.48   380.22042.811   385.5 2041.26
   425.1 2040.68   435.9 2042.54   487.4 2045.28   535.1 2045.82   557.1  2043.9
   725.7 2046.99     821 2050.18     843 2052.36     854 2055.06   864.6 2060.55
   912.6 2092.84   993.2 2128.03  1011.1 2134.16  1048.5 2142.93  1077.5 2154.15
  1110.5 2164.83  1128.9 2167.35    1151 2167.58  1187.2 2163.79  1212.7 2158.84
#Mann= 4 ,-1 , 0
       0    .035       0     260     .04       0   380.2    .045       0
   435.9      .1       0
#XS Ineff= 1 ,-1
  681.94  1212.6 2050.17
Permanent Ineff=
       F
Bank Sta=380.2,435.9
XS Rating Curve= 0 ,0
Exp/Cntr=0.3,0.1

Type RM Length L Ch R = 1 ,16179   ,463.6,482.6,487.9
XS GIS Cut Line= 2
     2156401.745      192774.381     2157109.917      191709.681
#Sta/Elev= 30
       0 2057.09   124.8 2055.28   206.8 2051.42     221    2046   254.1 2047.59
   274.5 2041.82   300.4 2043.44   325.8 2040.59   369.1  2039.4   386.6 2041.64
   432.1 2043.04   483.4 2041.68   504.92039.312   549.9 2037.93   557.42039.307
     583 2042.67   613.4 2043.49     654 2042.27   865.6 2042.84   897.1 2041.01
   932.6 2043.43   983.8 2043.08   994.8 2048.87  1015.3 2066.12  1050.8 2089.23
  1125.6 2149.06  1145.3 2160.59    1165 2168.86  1195.9 2177.84  1278.7 2192.59
#Mann= 11 ,-1 , 0
       0      .1       0      70    .035       0     150      .1       0
     190     .04       0     310      .1       0   504.9    .045       0
   557.4      .1       0     660    .035       0     780      .1       0
     860    .035       0     900      .1       0
#XS Ineff= 2 , 0
          299.07 2050.41  816.31         2049.19
Permanent Ineff=
       F       F
Bank Sta=504.9,557.4
XS Rating Curve= 0 ,0
Exp/Cntr=0.3,0.1

Type RM Length L Ch R = 1 ,15696   ,656.7,662.5,659
XS GIS Cut Line= 2
     2156494.567      193037.351     2157711.083       192193.15
#Sta/Elev= 30
       0 2057.72   120.8 2051.42   149.4 2048.42   189.4 2041.03   229.3 2042.26
   261.2 2040.52   275.2 2045.05   289.2 2045.88   301.2 2044.95   321.2 2037.53
     350 2038.65     437  2037.1   467.4 2039.57   512.8 2039.83   560.22038.136
   568.7 2036.16   608.8 2036.56   615.92038.178   652.6    2040   733.7 2040.15
   828.3 2038.24   856.3 2042.35   925.5 2045.14  1179.3 2051.81  1198.2 2059.07
  1239.6 2083.34  1254.7 2090.24  1383.4  2136.4  1415.3  2145.5  1480.7 2157.22
#Mann= 5 ,-1 , 0
       0      .1       0     230     .04       0     350      .1       0
   560.2    .045       0   615.9      .1       0
#XS Ineff= 2 , 0
          290.61 2048.85
Permanent Ineff=
       F       F
Bank Sta=560.2,615.9
XS Rating Curve= 0 ,0
Exp/Cntr=0.3,0.1