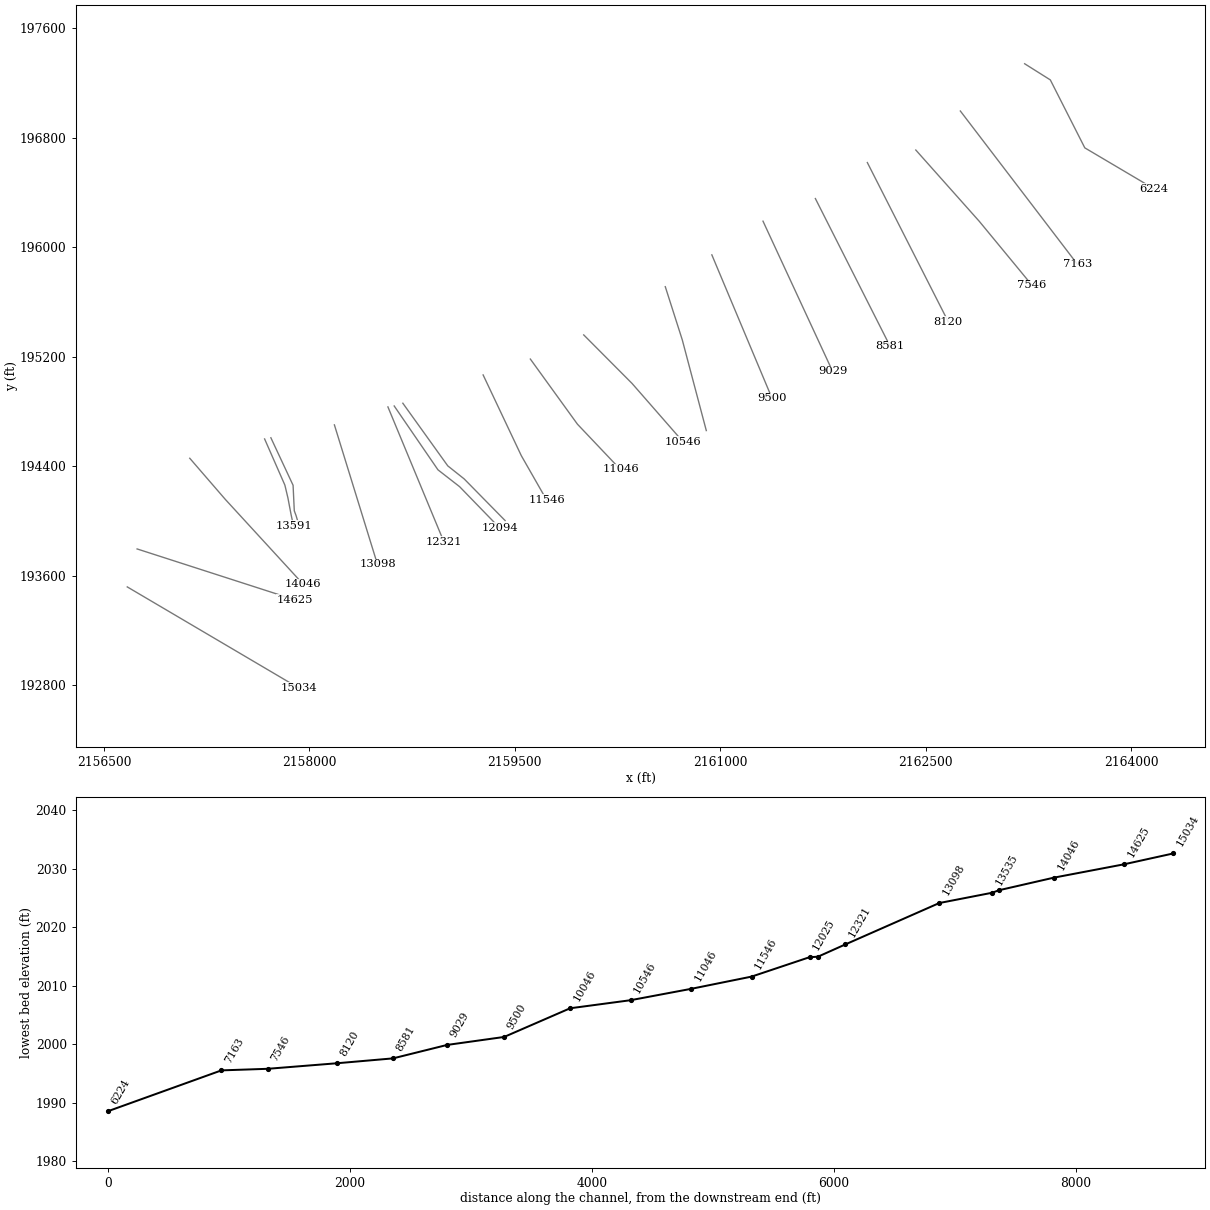
HEC-RAS study POTTSCK.prj: POTTSCK

--- POTTSCK.g01 (geometry) --- (continued)

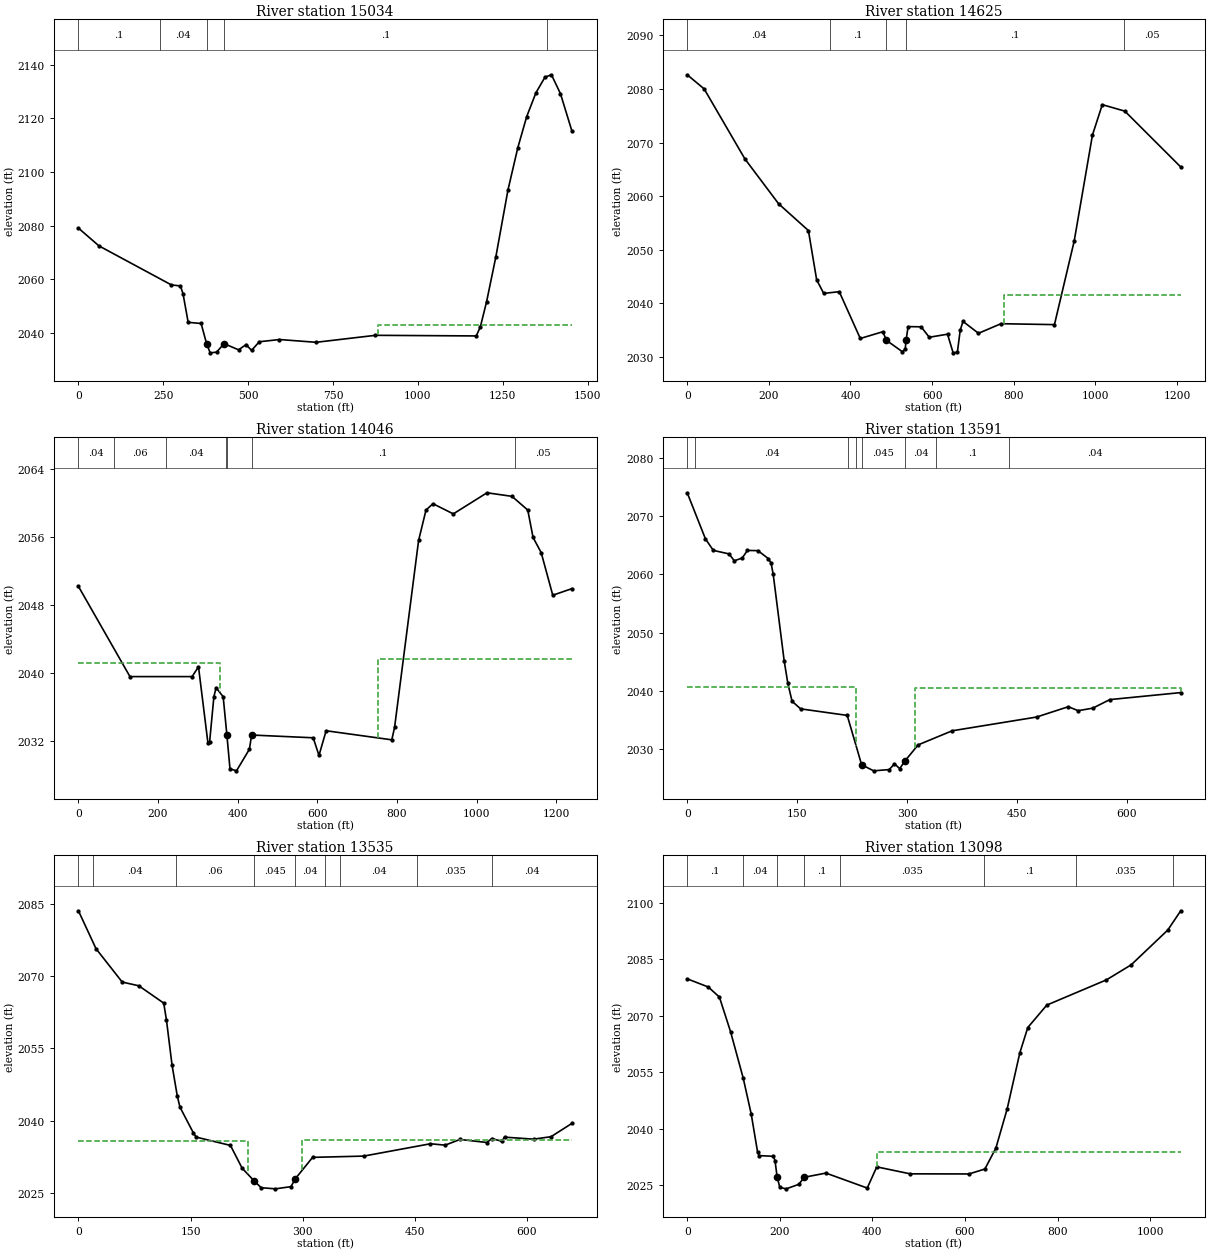
Type RM Length L Ch R = 1 ,15034   ,397,408.3,410.1
XS GIS Cut Line= 2
     2156670.116      193518.093     2157922.579      192779.589
#Sta/Elev= 30
       0 2079.07    60.6 2072.44   273.9  2057.9   300.6 2057.51   308.2 2054.63
   323.4 2043.95   361.5 2043.52  377.572036.052   388.2 2032.58   407.2 2032.83
     4292036.012   471.9  2033.7   494.2 2035.67     510 2033.47   532.9 2036.71
   592.4 2037.54   700.3 2036.51   875.2 2039.11  1172.3 2038.88  1184.4 2042.36
  1202.5 2051.58  1229.8  2068.3  1265.7 2093.36  1294.6 2109.04  1320.8 2120.63
  1347.9 2129.48  1374.6 2135.32  1393.7 2136.21  1420.3 2129.15    1454 2115.23
#Mann= 5 ,-1 , 0
       0      .1       0     240     .04       0  377.57    .045       0
     429      .1       0    1380     .04       0
#XS Ineff= 2 , 0
                          881.73         2043.11
Permanent Ineff=
       F       F
Bank Sta=377.57,429
XS Rating Curve= 0 ,0
Exp/Cntr=0.3,0.1

Type RM Length L Ch R = 1 ,14625   ,593.2,579.9,555.2
XS GIS Cut Line= 2
     2156742.032      193795.483     2157892.787      193424.271
#Sta/Elev= 30
       0 2082.65    41.4 2080.02   141.3 2066.94     224 2058.55   296.9 2053.56
   317.1 2044.36   334.4 2041.82   372.5 2042.14     424  2033.4   479.1 2034.66
   488.22033.046   527.4 2030.91   534.1 2031.43  536.222033.115   541.2 2035.62
   573.2 2035.58   592.9 2033.63   637.7  2034.2   651.5 2030.72   661.9 2030.84
   668.8 2034.94   675.6 2036.59   713.6 2034.37   768.7 2036.16   899.7 2035.99
     948 2051.57   992.8 2071.39  1016.9 2077.07  1072.1 2075.86  1209.1 2065.43
#Mann= 5 ,-1 , 0
       0     .04       0     350      .1       0   488.2    .045       0
  536.22      .1       0    1070     .05       0
#XS Ineff= 2 , 0
                          776.22         2041.45
Permanent Ineff=
       F       F
Bank Sta=488.2,536.22
XS Rating Curve= 0 ,0
Exp/Cntr=0.3,0.1

Type RM Length L Ch R = 1 ,14046   ,460.9,454.8,439.8
XS GIS Cut Line= 3
     2157126.554      194458.134     2157385.256      194158.584
     2157955.634      193536.879
#Sta/Elev= 30
       0 2050.21   129.5 2039.56   285.6 2039.56   301.6 2040.72   325.2 2031.77
   329.5 2031.83   340.3  2037.2   345.8 2038.24   363.6 2037.19   372.92032.681
   380.7 2028.68     397 2028.44   429.5 2030.99     4352032.666   589.7 2032.34
   604.2 2030.26   622.2 2033.17   787.1  2032.1   794.1 2033.57   854.4 2055.62
     873 2059.21   890.5 2059.96   941.6 2058.76  1026.2 2061.25    1089 2060.83
  1128.6 2059.21  1141.9 2055.98  1162.3 2054.19  1191.4 2049.16  1239.5 2049.94
#Mann= 7 ,-1 , 0
       0     .04       0      90     .06       0     220     .04       0
     370      .1       0   372.9    .045       0     435      .1       0
  1095.8     .05       0
#XS Ineff= 2 , 0
          355.01 2041.17  752.15         2041.61
Permanent Ineff=
       F       F
Bank Sta=372.9,435
XS Rating Curve= 0 ,0
Exp/Cntr=0.5,0.3

Type RM Length L Ch R = 1 ,13591   ,52.2,55.4,53
XS GIS Cut Line= 5
     2157673.139      194599.3482157821.24377074 194261.74017152
2157843.23905883 194168.940596642157866.32270465194047.136603265
2157884.07112367193963.759011887
#Sta/Elev= 30
       02074.006  24.8072066.105  35.555 2064.12  57.0512063.516  64.2162062.339
  74.964  2062.8  82.1292064.113   96.462064.073  110.792062.699 114.3732061.945
 117.3252059.989 132.2862045.148 137.2472041.302 143.0342038.229 154.6782036.923
  218.272035.802   237.92027.337 254.2872026.286 275.5922026.503 282.7572027.492
 289.9232026.656   296.62027.921 315.001 2030.74 361.3662033.157  476.512035.515
  519.922037.294 533.2772036.607 553.3132037.048 576.5472038.513 673.2542039.714
#Mann= 8 ,-1 , 0
       0      .1       0      10     .04       0     220     .06       0
     230     .04       0   237.9    .045       0   296.6     .04       0
     340      .1       0  438.67     .04       0
#XS Ineff= 2 , 0
          230.37 2040.74  311.17         2040.48
Permanent Ineff=
       F       F
Bank Sta=237.9,296.6
XS Rating Curve= 0 ,0
Exp/Cntr=0.5,0.3

Type RM Length L Ch R = 1 ,13535   ,441.4,437.8,432.6
XS GIS Cut Line= 5
     2157718.944      194607.8162157881.06512658194260.753659709
2157889.90509216194074.1556463292157902.91932955194039.151835408
 2157917.9090423193988.504570256
#Sta/Elev= 30
       02083.494  23.5562075.635   58.58 2068.72  80.7932067.946 114.0852064.361
 117.706 2060.92 125.2212051.527  132.192045.139 135.8112042.798 153.9172037.409
 157.5382036.579 203.324 2034.86 219.0122030.132   234.72027.564 244.4452026.095
 263.4392025.861 284.2782026.313   290.12027.957 313.2472032.385  381.622032.647
 470.8242035.204 490.5312034.914 510.2382036.098 546.3682035.465 552.9372036.292
 566.0752035.717 569.8682036.574 608.9812036.156 632.102 2036.67 660.0322039.425
#Mann= 9 ,-1 , 0
       0      .1       0      20     .04       0     130     .06       0
   234.7    .045       0   290.1     .04       0     330    .035       0
     350     .04       0  453.06    .035       0  553.06     .04       0
#XS Ineff= 2 , 0
          226.93 2035.83  299.14         2035.98
Permanent Ineff=
       F       F
Bank Sta=234.7,290.1
XS Rating Curve= 0 ,0
Exp/Cntr=0.5,0.3

Type RM Length L Ch R = 1 ,13098   ,752.9,776.4,755.3
XS GIS Cut Line= 2
     2158182.784      194702.116     2158497.077      193683.575
#Sta/Elev= 30
       0 2079.83    45.5 2077.66    69.5 2074.99    93.6  2065.8     121 2053.45
   138.2 2043.96   151.9  2033.9   155.4 2032.92   186.3 2032.73   189.7  2031.5
  194.132027.281     200 2024.47   213.7  2024.1   241.2  2025.3   252.52027.168
   299.6 2028.28   388.8 2024.31   409.4 2029.93   481.5 2028.08   608.6 2028.05
   642.9 2029.36   666.7 2034.94     691  2045.3   718.4 2060.21   735.6 2066.91
   776.6 2072.86   905.5 2079.56   958.8 2083.54  1037.8 2092.76  1065.9 2097.89
#Mann= 8 ,-1 , 0
       0      .1       0     120     .04       0  194.13    .045       0
   252.5      .1       0     330    .035       0     640      .1       0
     840    .035       0    1050      .1       0
#XS Ineff= 2 , 0
                          409.91         2033.92
Permanent Ineff=
       F       F
Bank Sta=194.13,252.5
XS Rating Curve= 0 ,0
Exp/Cntr=0.3,0.1

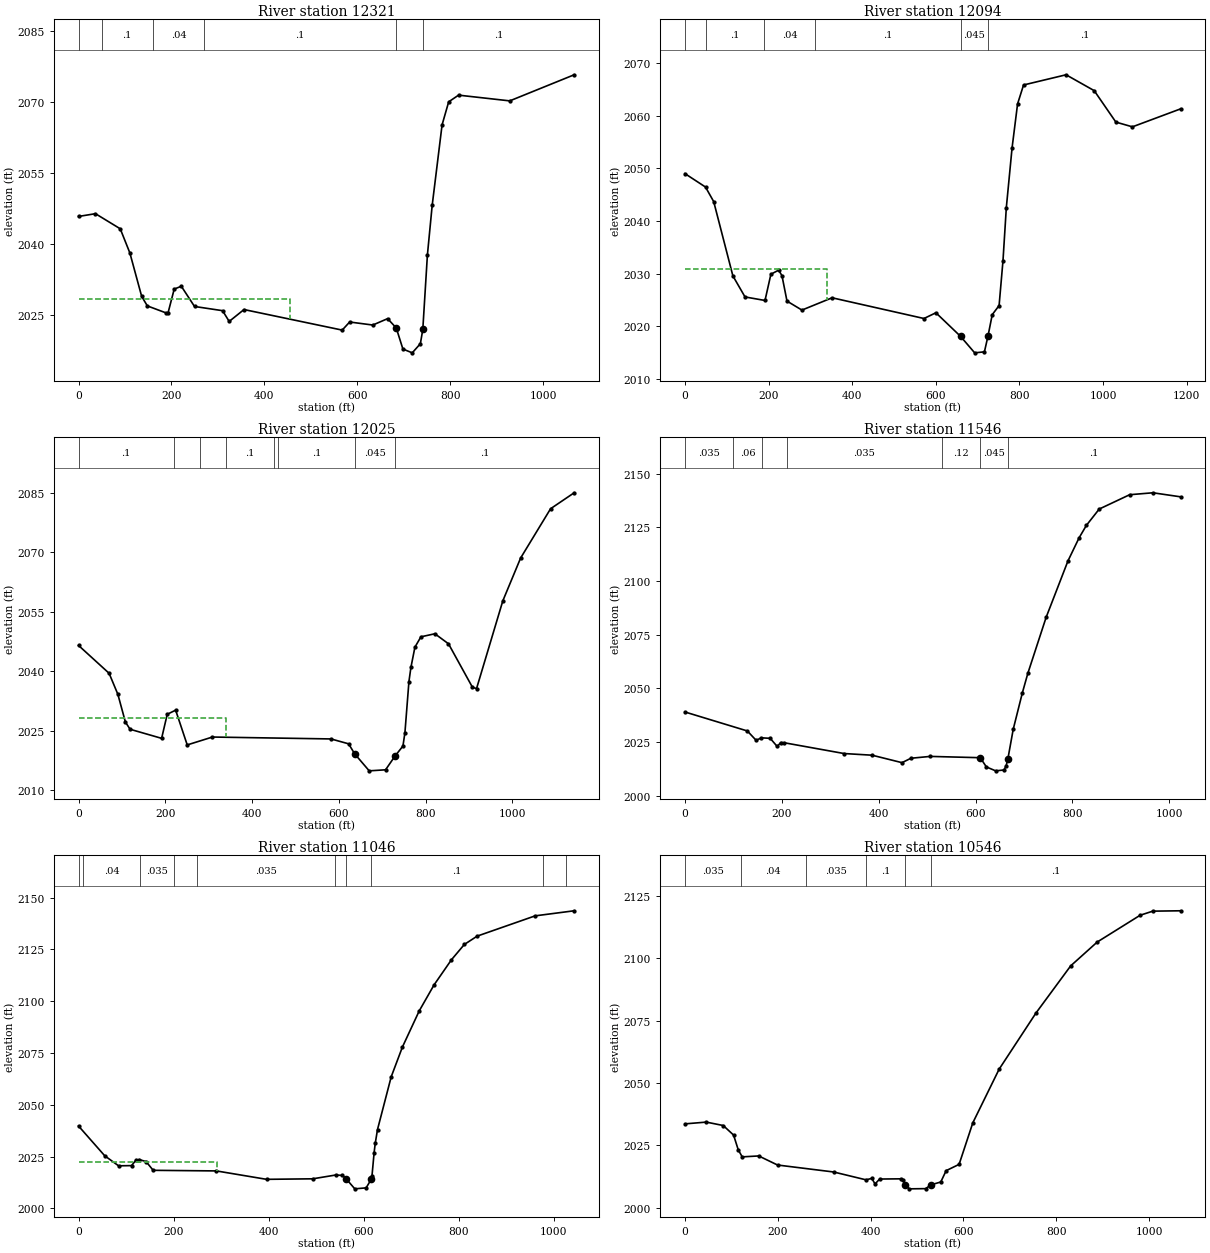
Type RM Length L Ch R = 1 ,12321   ,208.4,226.9,246
XS GIS Cut Line= 2
     2158573.643      194833.444     2158982.034      193848.253
#Sta/Elev= 30
       0 2045.83    36.5 2046.41    89.8 2043.22   110.5 2038.12   135.9 2028.95
   148.1 2026.94   189.2 2025.43   192.8 2025.52   205.9 2030.49   221.2 2031.09
   249.6 2026.82     310 2025.93   324.2 2023.66   356.1 2026.17   567.4 2021.83
   583.4 2023.54   633.2  2022.9   665.1 2024.25   683.72022.283     698 2017.83
   718.1 2017.03   735.6 2018.96  740.82 2021.99   750.7 2037.68     761 2048.17
   782.3 2065.17   796.5 2070.03   817.8 2071.44   927.9 2070.23  1066.5 2075.74
#Mann= 6 ,-1 , 0
       0     .12       0      50      .1       0     160     .04       0
     270      .1       0   683.7    .045       0  740.82      .1       0
#XS Ineff= 2 , 0
          455.73 2028.33
Permanent Ineff=
       F       F
Bank Sta=683.7,740.82
XS Rating Curve= 0 ,0
Exp/Cntr=0.5,0.3

Type RM Length L Ch R = 1 ,12094   ,68.8,68.8,77.2
XS GIS Cut Line= 4
  2158619.480468194840.2253072112158939.11872603194373.626930543
2159097.10085357194250.5478311852159389.18408936193949.279587982
#Sta/Elev= 30
       0 2049.01    49.1 2046.46    68.7 2043.69   114.6 2029.56   143.6 2025.56
   191.4 2024.89   205.5 2029.88   224.1 2030.66     232  2029.6     244 2024.77
   279.7 2023.06   351.9  2025.4   571.6 2021.46   600.2 2022.55     6592018.072
   692.9 2014.93   716.2 2015.12   724.9 2018.18   734.9 2022.19   751.3 2023.92
   760.6 2032.44   768.6 2042.56   782.3 2053.88   795.5 2062.27   809.8 2065.87
   911.5 2067.81   978.8 2064.79  1030.6 2058.81  1070.2 2057.91  1185.5 2061.33
#Mann= 6 ,-1 , 0
       0     .12       0      50      .1       0     190     .04       0
     310      .1       0     659    .045       0   724.9      .1       0
#XS Ineff= 2 , 0
           340.4 2030.82
Permanent Ineff=
       F       F
Bank Sta=659,724.9
XS Rating Curve= 0 ,0
Exp/Cntr(USF)=0,0
Exp/Cntr=0.5,0.3

Type RM Length L Ch R = 1 ,12025   ,493.3,479.9,447.8
XS GIS Cut Line= 4
2158682.58079832 194860.303924372159010.65794661194402.651062284
2159130.16688026194307.4948771562159429.23712457194003.034028176
#Sta/Elev= 30
       0  2046.5    70.5 2039.47    90.7 2034.17   108.1 2027.16   118.9 2025.34
   191.6 2023.05   204.5 2029.12   223.9 2030.16   250.6 2021.39   308.7 2023.38
     582  2022.9   622.6 2021.67 636.5472019.151   670.1 2014.85   707.8 2015.11
  729.512018.561   747.9 2021.11   752.5 2024.52   761.7 2037.38   766.3 2040.97
   775.5 2046.06   789.3 2048.67   821.5 2049.44   852.9 2046.91   908.2 2035.92
   917.6 2035.62   978.1 2057.74  1019.2 2068.56  1088.2 2080.99  1142.6 2085.02
#Mann= 8 ,-1 , 0
       0      .1       0     220     .04       0     280    .035       0
     340      .1       0     450    .035       0     460      .1       0
 636.547    .045       0  729.51      .1       0
#XS Ineff= 2 , 0
           340.4 2028.22
Permanent Ineff=
       F       F
Bank Sta=636.547,729.51
XS Rating Curve= 0 ,0
Exp/Cntr=0.5,0.3

Type RM Length L Ch R = 1 ,11546   ,489.5,500,506.5
XS GIS Cut Line= 3
     2159268.917      195067.094     2159547.601      194477.311
     2159731.621      194155.046
#Sta/Elev= 30
       0 2038.94   128.8  2030.1   146.9 2025.74   157.8 2026.91     176 2026.67
   190.4 2022.88   197.7 2024.71     205 2024.61   328.5 2019.59   386.4 2018.81
   448.1 2015.34   466.5 2017.39   506.2 2018.25   609.72017.649   622.3 2013.35
   641.4 2011.53   658.8 2011.93   663.3    2014  666.84 2017.25   677.7 2030.85
   696.6 2047.86     708    2057   745.7 2083.03   790.8 2109.32   813.7 2120.04
   828.8 2125.86   855.3 2133.46   918.2 2140.14   966.3 2141.04  1023.4 2139.15
#Mann= 7 ,-1 , 0
       0    .035       0     100     .06       0     160     .04       0
     210    .035       0     530     .12       0   609.7    .045       0
  666.84      .1       0
Bank Sta=609.7,666.84
XS Rating Curve= 0 ,0
Exp/Cntr=0.3,0.1

Type RM Length L Ch R = 1 ,11046   ,494.6,500,498
XS GIS Cut Line= 3
     2159613.797       195183.02     2159957.654      194707.183
     2160271.536      194376.025
#Sta/Elev= 30
       0 2039.78    55.2  2025.4    84.3 2020.56   111.6 2020.65   120.7 2023.21
   128.1 2023.55   142.2 2022.61   157.2 2018.38   290.2 2018.09   395.9 2014.03
   493.1 2014.28   541.6 2016.12   555.7 2015.91  563.122014.355   581.6 2009.44
   605.5 2009.91   616.42014.149   617.8 2015.73   622.3 2026.97   624.6 2031.33
   629.4 2038.07   658.2  2063.5   681.8 2077.87   717.2 2095.33   748.6 2107.95
     785 2120.01   812.2 2127.42   839.2 2131.44   961.3 2141.23  1043.4 2143.68
#Mann= 10 ,-1 , 0
       0    .035       0      10     .04       0     130    .035       0
     200     .04       0     250    .035       0     540      .1       0
  563.12    .045       0   616.4      .1       0  977.08     .12       0
 1027.08      .1       0
#XS Ineff= 2 , 0
          292.26 2022.16
Permanent Ineff=
       F       F
Bank Sta=563.12,616.4
XS Rating Curve= 0 ,0
Exp/Cntr=0.3,0.1

Type RM Length L Ch R = 1 ,10546   ,513.8,500,481.5
XS GIS Cut Line= 3
     2160003.583      195359.545     2160356.542      195004.756
     2160729.839      194577.392
#Sta/Elev= 30
       0 2033.57    45.9 2034.28    82.4 2032.91   104.7 2029.08   114.8 2023.15
   123.3 2020.33   158.9  2020.7   199.4 2017.06   320.4 2014.26   390.1 2011.11
   402.5  2011.7   409.5 2009.46   419.4 2011.43   465.7 2011.52   469.8 2011.11
   474.3 2009.12   483.2  2007.5   518.5 2007.58     5302009.117   551.1 2010.24
   562.7  2014.8   590.6 2017.32   620.2 2034.01   676.8  2055.5   756.2 2078.05
     831 2096.97   888.2 2106.54   980.7 2117.29  1007.9 2118.93  1067.9 2119.08
#Mann= 6 ,-1 , 0
       0    .035       0     120     .04       0     260    .035       0
     390      .1       0   474.3    .045       0     530      .1       0
Bank Sta=474.3,530
XS Rating Curve= 0 ,0
Exp/Cntr=0.3,0.1

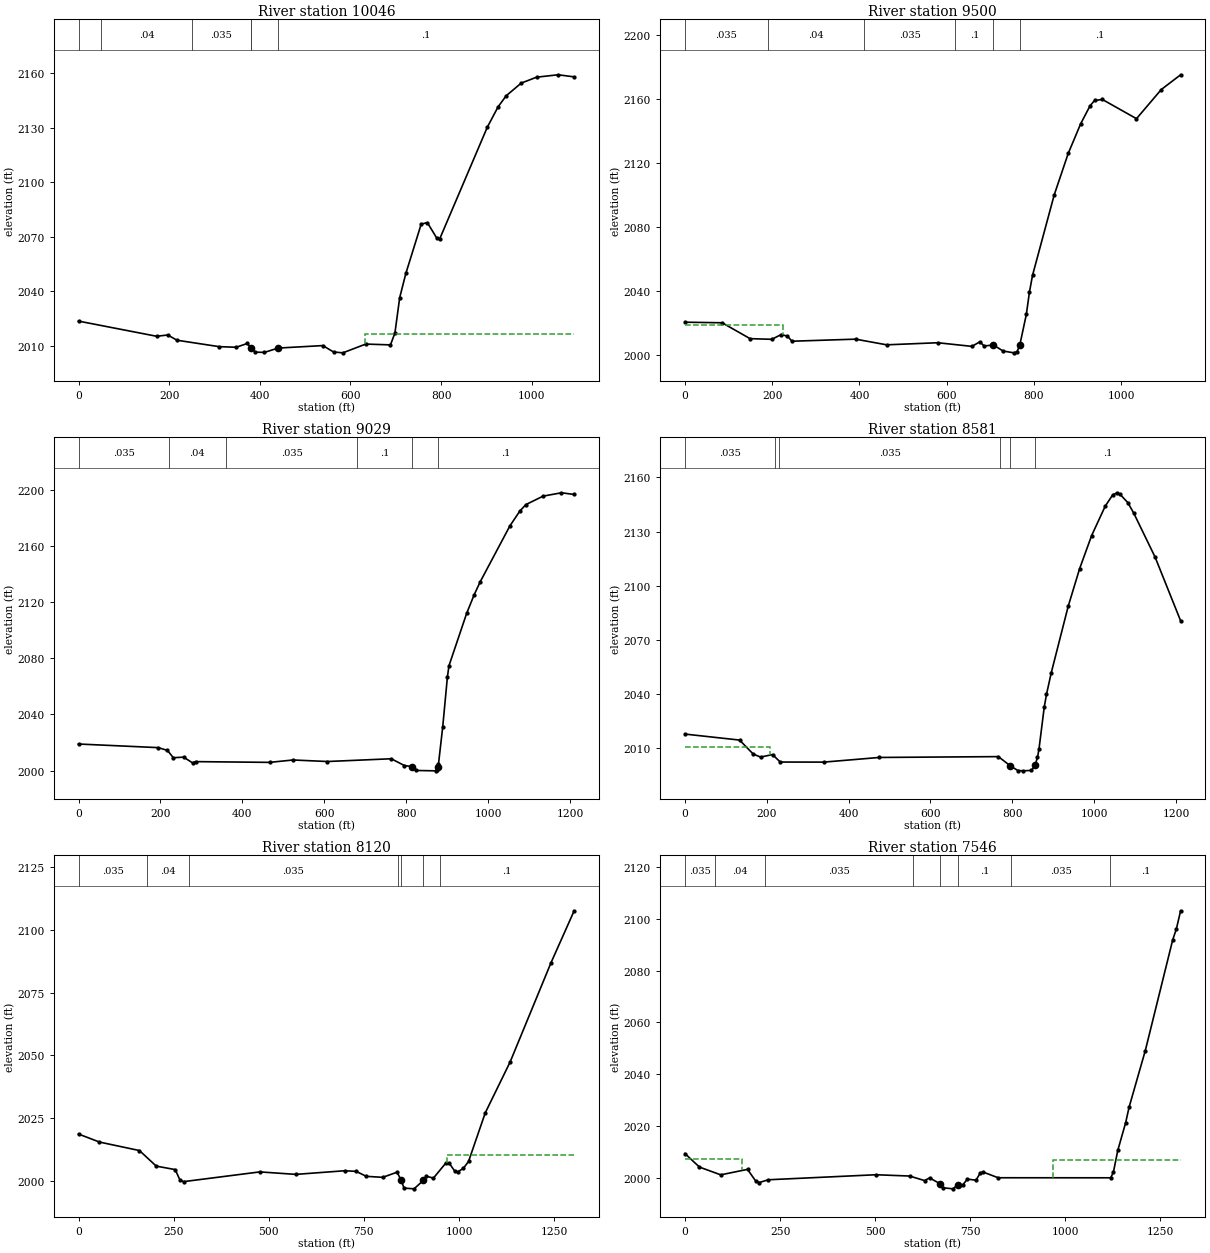
Type RM Length L Ch R = 1 ,10046   ,533.7,545.6,542.8
XS GIS Cut Line= 3
     2160599.086      195712.036     2160723.174      195323.584
      2160898.64      194660.494
#Sta/Elev= 30
       0 2023.57   172.5 2015.22   196.9 2015.94   217.2 2013.06   310.2 2009.52
   348.1 2009.19   372.2 2011.26   381.72008.679   390.1 2006.52   410.1 2006.35
   440.42008.739     539 2010.11   562.8 2006.59   583.2 2006.12   633.8 2010.94
   688.4 2010.49   698.2 2017.06   708.7 2036.45   722.3 2049.79   756.2 2076.94
   769.8  2077.7   790.2 2069.35     797 2068.77   902.1 2130.21   925.9 2141.41
   943.7 2147.45   976.8 2154.41  1010.8 2157.68  1058.3    2159  1093.7 2157.85
#Mann= 6 ,-1 , 0
       0    .035       0      50     .04       0     250    .035       0
     380      .1       0   381.7    .045       0   440.4      .1       0
#XS Ineff= 2 , 0
                          632.82         2016.22
Permanent Ineff=
       F       F
Bank Sta=381.7,440.4
XS Rating Curve= 0 ,0
Exp/Cntr=0.3,0.1

Type RM Length L Ch R = 1 ,9500    ,470.2,470.9,473
XS GIS Cut Line= 2
     2160939.151       195944.53     2161378.542      194896.753
#Sta/Elev= 30
       0 2020.36    85.2 2020.01   149.2 2010.09     199 2009.67   220.3 2012.61
   234.7 2011.71   245.3 2008.48   391.1 2009.77   462.3 2006.23   579.7 2007.53
   657.9 2005.25   675.7  2008.1   685.9 2005.51   707.22006.126   729.1 2002.36
     754 2001.22   761.2 2001.93  767.41 2005.94   782.5 2025.23   789.6 2039.15
   796.7 2049.66   846.5 2099.99   878.5 2125.81     907 2144.31   928.3 2155.46
   938.8  2158.9   956.8 2159.54    1035 2147.54  1091.9 2165.77  1136.2 2174.97
#Mann= 6 ,-1 , 0
       0    .035       0     190     .04       0     410    .035       0
     620      .1       0   707.2    .045       0  767.41      .1       0
#XS Ineff= 2 , 0
          225.39 2018.85
Permanent Ineff=
       F       F
Bank Sta=707.2,767.41
XS Rating Curve= 0 ,0
Exp/Cntr=0.3,0.1

Type RM Length L Ch R = 1 ,9029    ,445.9,447.9,448.4
XS GIS Cut Line= 2
     2161312.687      196190.742     2161821.044      195093.154
#Sta/Elev= 30
       0 2018.96   194.8 2016.38   217.1 2014.39   231.3 2009.21   256.5  2009.6
   278.3 2005.53   285.6 2006.42   466.6 2005.89   523.5 2007.59   607.5  2006.5
   763.2 2008.46   795.3 2003.63   814.52002.851   824.3 2000.12   871.3 1999.86
   874.9 2000.31  876.562002.241   878.5 2004.69   888.8 2031.13   900.2 2066.52
     904 2074.63   947.2 2111.96   965.8 2125.39   980.6 2134.63  1052.7 2174.23
    1077 2184.82  1091.8 2189.43  1133.8 2195.45  1178.6 2197.84  1209.6 2196.63
#Mann= 6 ,-1 , 0
       0    .035       0     220     .04       0     360    .035       0
     680      .1       0   814.5    .045       0  876.56      .1       0
Bank Sta=814.5,876.56
XS Rating Curve= 0 ,0
Exp/Cntr=0.3,0.1

Type RM Length L Ch R = 1 ,8581    ,460.7,461.5,461
XS GIS Cut Line= 2
     2161695.148      196355.978     2162241.847      195274.865
#Sta/Elev= 30
       0 2017.91   133.4 2014.59   166.7 2006.87   184.7 2005.18     214 2006.56
   232.9 2002.43   339.5 2002.39   475.2 2004.97     766 2005.43   795.62000.264
   813.8 1997.72   826.8 1997.56   846.9 1997.81  855.472000.518   861.6 2005.01
   865.2 2009.47   878.1 2032.79   883.6 2039.84   895.2 2051.78   936.7 2088.66
   964.5  2109.4   993.9 2127.77  1027.1 2144.04  1045.4  2150.3  1056.2 2151.48
  1063.8 2150.53  1082.2 2146.09  1096.9 2140.21  1149.1 2115.86  1211.5 2080.59
#Mann= 6 ,-1 , 0
       0    .035       0     220     .04       0     230    .035       0
     770      .1       0   795.6    .045       0  855.47      .1       0
#XS Ineff= 2 , 0
           206.6 2010.71
Permanent Ineff=
       F       F
Bank Sta=795.6,855.47
XS Rating Curve= 0 ,0
Exp/Cntr=0.3,0.1

Type RM Length L Ch R = 1 ,8120    ,563.4,574,582.2
XS GIS Cut Line= 2
     2162074.669      196619.009      2162664.75      195457.482
#Sta/Elev= 30
       0  2018.6    55.1  2015.4   160.1 2012.01   204.3  2005.8   254.1 2004.41
   266.9 2000.18     276  1999.6   476.6 2003.49   571.3  2002.5   699.7 2003.95
   729.9  2003.7   756.3 2001.72   799.7 2001.32   837.3 2003.38   847.8 2000.22
   855.6 1997.03     882 1996.73   906.72000.144   914.5 2001.76   932.9 2001.01
     966 2007.12   973.9 2007.05   989.5 2003.69   996.7 2003.51  1011.2 2004.85
  1025.2 2007.67  1069.1 2027.05  1134.4 2047.34    1242 2086.99  1302.8  2107.7
#Mann= 7 ,-1 , 0
       0    .035       0     180     .04       0     290    .035       0
     840     .12       0   847.8    .045       0   906.7     .12       0
     950      .1       0
#XS Ineff= 2 , 0
                          968.01         2010.27
Permanent Ineff=
       F       F
Bank Sta=847.8,906.7
XS Rating Curve= 0 ,0
Exp/Cntr=0.3,0.1

Type RM Length L Ch R = 1 ,7546    ,384.4,382.9,382.5
XS GIS Cut Line= 3
     2162428.601        196710.6     2162892.332      196189.432
     2163277.473      195722.067
#Sta/Elev= 30
       0 2009.39    38.1 2004.17    94.1 2001.18   164.4 2003.29   186.3 1998.72
   195.1  1998.2   218.8 1999.28   502.3 2001.22   590.6 2000.72   629.9 1998.97
   643.1    2000   671.41997.689   678.2 1996.21   704.7 1995.78   717.2 1997.35
   729.8  1997.2   742.6 1999.54   765.1 1999.11   776.9 2002.02   783.8 2002.26
   823.4 2000.06  1119.4 2000.04  1126.4  2002.2    1138 2010.64  1158.7 2021.33
  1167.7  2027.3  1210.3 2049.13  1282.5 2091.95  1291.8 2095.98  1303.2 2103.09
#Mann= 8 ,-1 , 0
       0    .035       0      80     .04       0     210    .035       0
     600      .1       0   671.4    .045       0   717.2      .1       0
  857.61    .035       0 1117.61      .1       0
#XS Ineff= 2 , 0
          150.26 2007.43  966.56         2006.72
Permanent Ineff=
       F       F
Bank Sta=671.4,717.2
XS Rating Curve= 0 ,0
Exp/Cntr=0.3,0.1

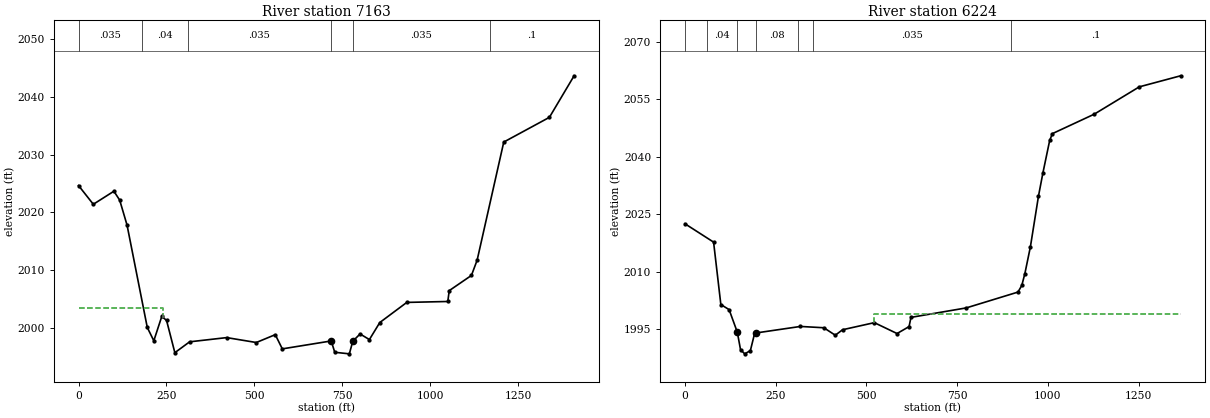
Type RM Length L Ch R = 1 ,7163    ,918.8,938.7,947.3
XS GIS Cut Line= 2
     2162753.806      196995.823     2163608.713      195875.855
#Sta/Elev= 30
       0 2024.64    42.1 2021.39   100.6 2023.65   117.1 2022.11     138 2017.79
   195.5 2000.08   214.1 1997.77   236.8    2002   250.4 2001.28   273.9 1995.71
   315.9 1997.59   421.3 1998.32   505.5 1997.47   559.4 1998.83   579.4 1996.37
   718.51997.741   728.5 1995.78     770 1995.51   779.81997.694   800.5 1998.95
     827 1997.98   856.6 2000.93   933.3 2004.41  1049.9 2004.57    1054 2006.45
  1117.1 2009.08  1133.3 2011.72    1209 2032.16  1338.8 2036.44    1409 2043.63
#Mann= 6 ,-1 , 0
       0    .035       0     180     .04       0     310    .035       0
   718.5    .045       0   779.8    .035       0    1170      .1       0
#XS Ineff= 2 , 0
          241.07 2003.48
Permanent Ineff=
       F       F
Bank Sta=718.5,779.8
XS Rating Curve= 0 ,0
Exp/Cntr=0.5,0.3

Type RM Length L Ch R = 1 ,6224    ,63.5,64.1,70
XS GIS Cut Line= 4
     2163223.443      197341.097     2163410.943      197223.041
     2163662.679      196726.514     2164168.589      196427.098
#Sta/Elev= 30
       0 2022.47    78.7 2017.69    98.7  2001.4   121.5 2000.07  144.061994.185
     153  1989.6   164.6 1988.53   180.1 1989.37   191.7 1993.83   194.31993.961
   318.1 1995.68   382.5 1995.34   414.2 1993.39   434.2 1994.82   521.8 1996.67
   584.4 1993.83   617.5 1995.64   622.8 1998.05   775.2 2000.52   917.7 2004.65
   928.3 2006.39   936.8  2009.5     952 2016.48   974.3 2029.73   986.4 2035.73
  1005.1 2044.22  1012.6 2046.01    1128 2051.09  1252.1 2058.22  1366.1 2061.11
#Mann= 7 ,-1 , 0
       0    .035       0      60     .04       0  144.06    .045       0
   194.3     .08       0  311.57     .04       0  351.57    .035       0
  898.27      .1       0
#XS Ineff= 2 , 0
                          521.57            1999
Permanent Ineff=
       F       F
Bank Sta=144.06,194.3
XS Rating Curve= 0 ,0
Exp/Cntr=0.5,0.3