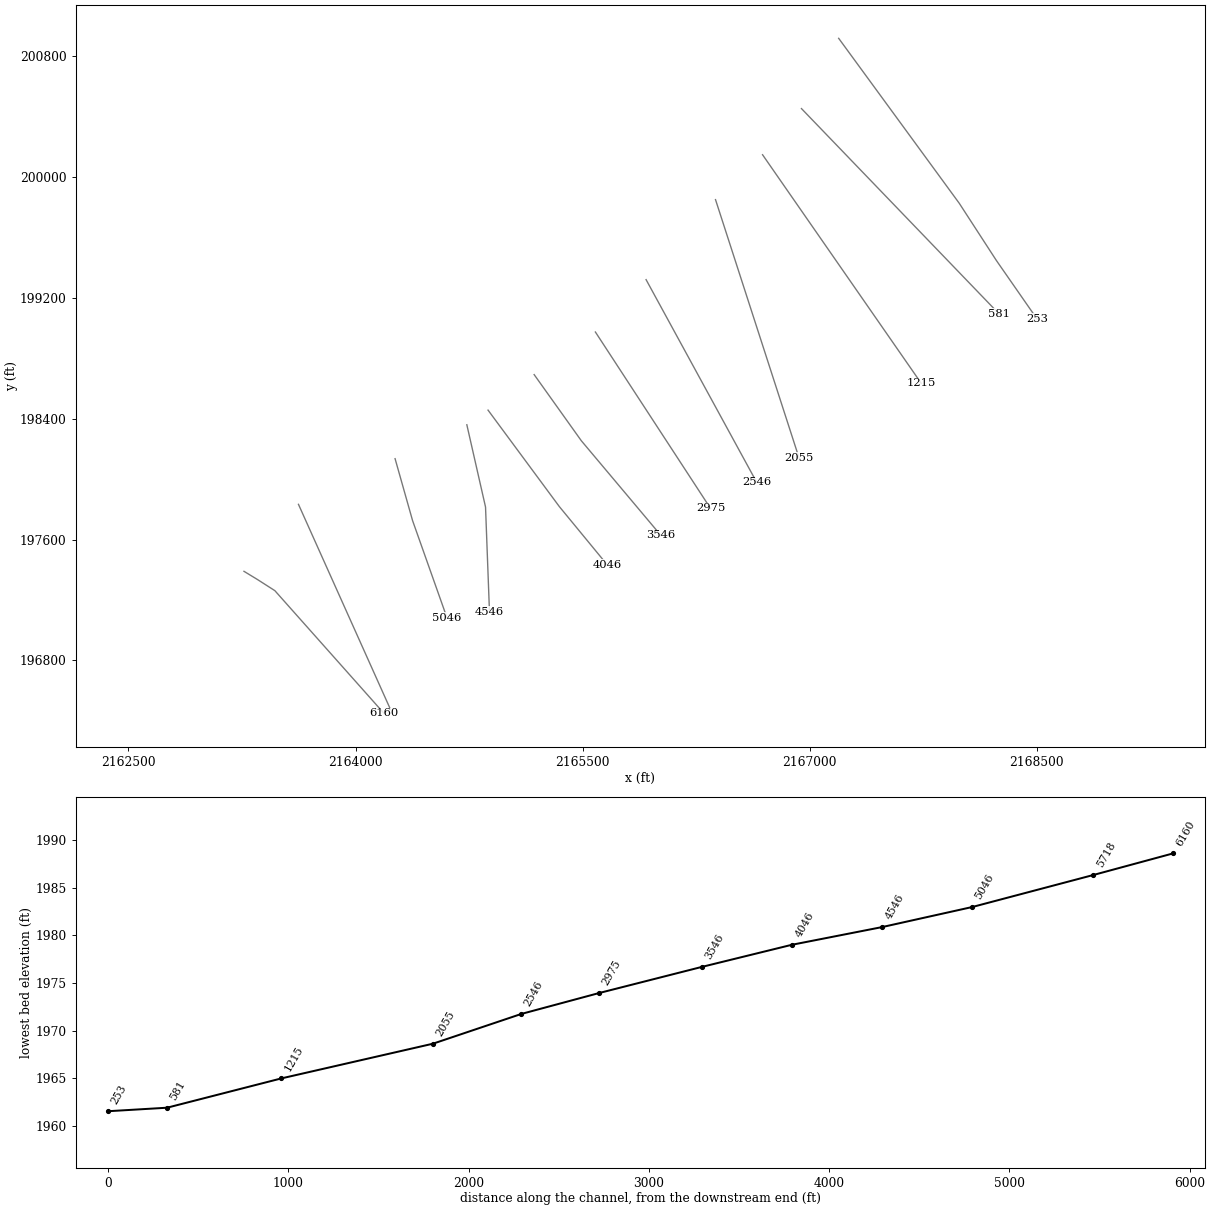
HEC-RAS study POTTSCK.prj: POTTSCK

--- POTTSCK.g01 (geometry) --- (continued)

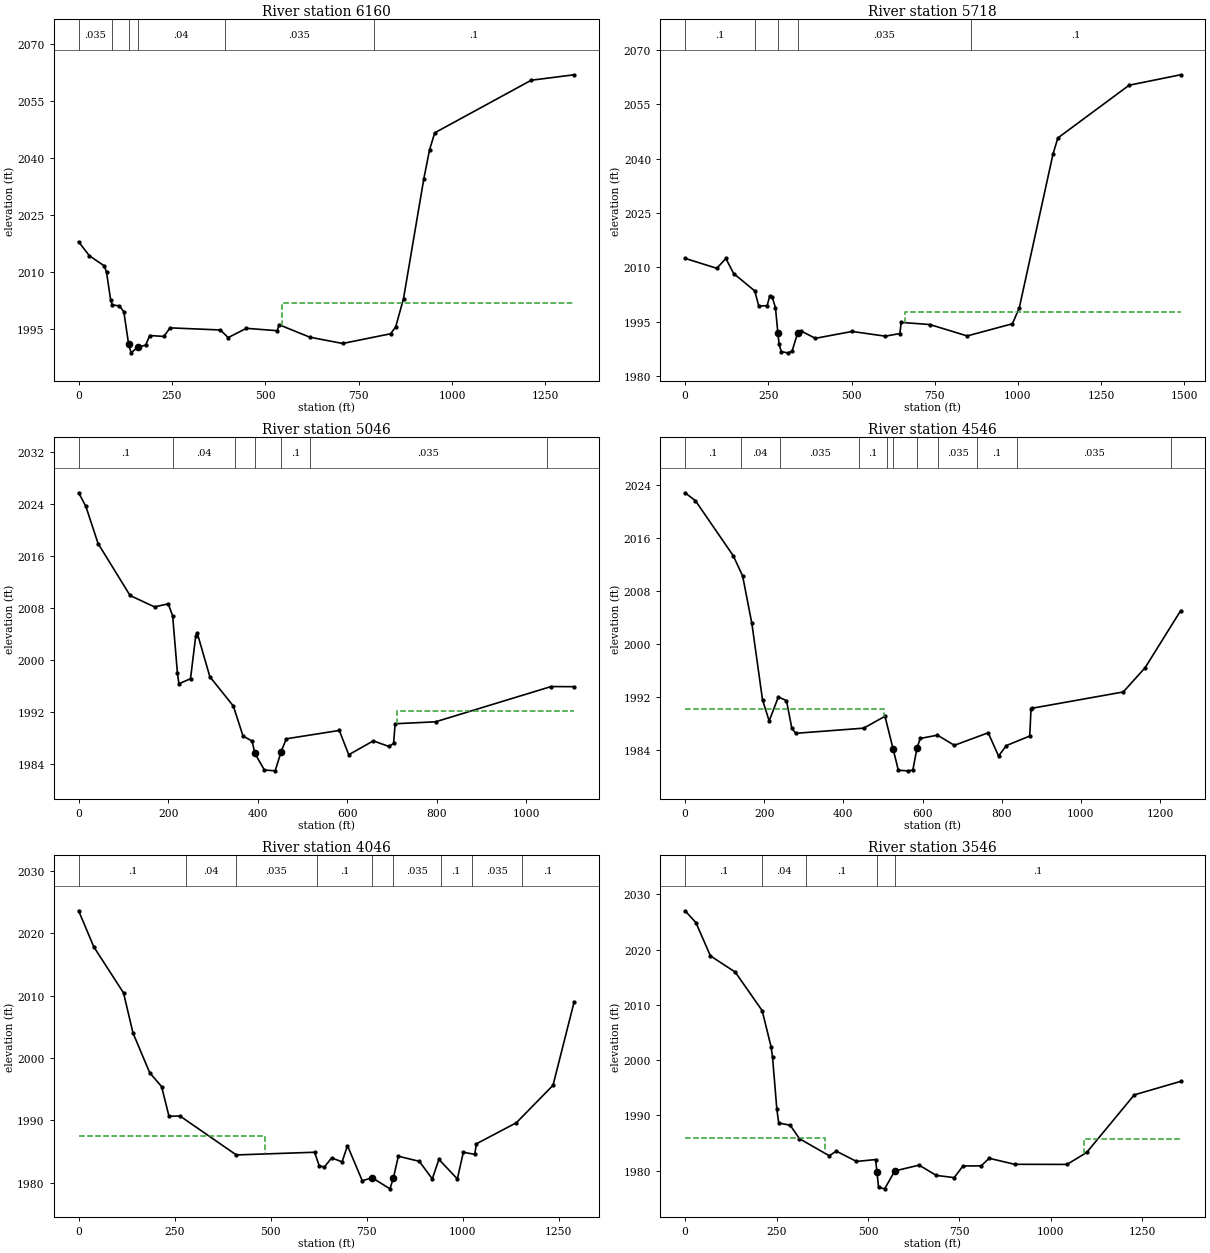
Type RM Length L Ch R = 1 ,6160    ,454.2,442.2,429.6
XS GIS Cut Line= 4
2163262.80511638197389.7588262012163351.75305884197335.522275918
2163466.73454545197261.7605675322164187.64766459196449.282164577
#Sta/Elev= 30
       0 2017.92    28.7 2014.24      69 2011.55    74.8 2009.83    85.7 2002.61
    90.1 2001.27   109.4 2001.01   121.1 1999.43     134 1990.83   140.6 1988.63
   158.3 1990.11   179.6 1990.67   190.3  1993.2   228.3 1992.95   244.8 1995.22
   379.6 1994.66   400.4 1992.65   449.3  1995.1   532.2 1994.46   536.5 1996.06
     619 1992.76   706.9  1991.1   835.5 1993.66   849.1 1995.48     870 2002.94
   924.4 2034.55   939.7 2042.18   953.6 2046.66    1212 2060.53    1327 2061.97
#Mann= 6 ,-1 , 0
       0    .035       0      90     .04       0     134    .045       0
   158.3     .04       0  390.79    .035       0  790.79      .1       0
#XS Ineff= 2 , 0
                          543.44         2001.82
Permanent Ineff=
       F       F
Bank Sta=134,158.3
XS Rating Curve= 0 ,0
Exp/Cntr(USF)=0,0
Exp/Cntr=0.5,0.3

Type RM Length L Ch R = 1 ,5718    ,671.8,672.2,662.5
XS GIS Cut Line= 2
     2163622.759      197833.152     2164231.062      196474.179
#Sta/Elev= 30
       0 2012.46    95.2 2009.72   122.5 2012.43   145.9 2008.28   209.4 2003.46
   221.4 1999.27   246.5  1999.4   254.1 2001.97   261.5  2001.8   271.5 1998.86
   278.81991.758   282.5 1988.75   288.9  1986.7   307.7 1986.36   321.1 1986.77
   337.81991.715   347.2 1992.45   391.4 1990.37   501.8 1992.27   601.7 1990.96
   645.5  1991.7   649.1 1994.77   735.4 1994.18   847.5 1991.03   983.4 1994.39
    1004 1998.76  1105.6 2041.37    1120 2045.73  1334.2 2060.31  1488.9 2063.19
#Mann= 5 ,-1 , 0
       0      .1       0     210     .04       0   278.8    .045       0
   337.8    .035       0     860      .1       0
#XS Ineff= 2 , 0
                          662.13         1997.74
Permanent Ineff=
       F       F
Bank Sta=278.8,337.8
XS Rating Curve= 0 ,0
Exp/Cntr=0.3,0.1

Type RM Length L Ch R = 1 ,5046    ,500.7,500,489.4
XS GIS Cut Line= 3
     2164260.869      198135.415     2164376.518      197725.236
     2164603.313      197083.371
#Sta/Elev= 30
       0 2025.68    16.1  2023.6    43.4 2017.89   114.9 2009.91   169.5 2008.16
   200.2 2008.63     210 2006.77   220.6 1998.06     224 1996.36   249.9 1997.13
   261.5 2003.66   264.9 2004.16   293.1 1997.44   345.6 1992.94   367.2 1988.34
   387.6 1987.55   393.4 1985.71   414.9 1983.12     439 1982.99   452.41985.945
   463.9 1987.91   582.2 1989.19   603.4 1985.46   658.2 1987.59     693 1986.73
   703.5 1987.19     707 1990.22   797.4 1990.52  1055.3 1995.93  1106.9 1995.91
#Mann= 7 ,-1 , 0
       0      .1       0     210     .04       0     350      .1       0
   393.4    .045       0   452.4      .1       0  516.17    .035       0
 1046.17      .1       0
#XS Ineff= 2 , 0
                          710.84         1992.16
Permanent Ineff=
       F       F
Bank Sta=393.4,452.4
XS Rating Curve= 0 ,0
Exp/Cntr=0.3,0.1

Type RM Length L Ch R = 1 ,4546    ,485,500,518.6
XS GIS Cut Line= 3
     2164734.878      198359.946     2164858.357       197815.36
     2164884.381      197122.046
#Sta/Elev= 30
       0 2022.83    26.2 2021.63   121.6 2013.34   145.3  2010.3   168.7 2003.11
   195.6  1991.6   212.5  1988.4   235.6 1992.02   256.2 1991.48   269.7  1987.3
   279.5 1986.54   451.3 1987.32   505.1 1989.11   525.81984.146   538.8 1980.97
   562.2 1980.88   575.4 1980.97  586.031984.327   594.2 1985.77   637.8 1986.26
   680.4 1984.73   765.8 1986.62   792.1 1983.12   811.8 1984.69   870.9 1986.13
   874.1 1990.22   877.4 1990.33  1107.2 1992.78  1162.3 1996.43  1252.2 2005.04
#Mann= 11 ,-1 , 0
       0      .1       0     140     .04       0     240    .035       0
     440      .1       0     510    .035       0   525.8    .045       0
  586.03      .1       0  638.41    .035       0  738.41      .1       0
  838.41    .035       0 1228.41      .1       0
#XS Ineff= 2 , 0
          502.79 1990.22
Permanent Ineff=
       F       F
Bank Sta=525.8,586.03
XS Rating Curve= 0 ,0
Exp/Cntr=0.3,0.1

Type RM Length L Ch R = 1 ,4046    ,482.4,500,483.5
XS GIS Cut Line= 3
     2164874.908      198456.931     2165345.731      197818.435
     2165661.039      197434.231
#Sta/Elev= 30
       0 2023.63    39.6 2017.83   116.9 2010.46   141.5 2004.03   184.9 1997.67
   216.1 1995.41   235.3 1990.66   263.8 1990.71   410.6 1984.46   614.4 1984.89
   626.6 1982.68   640.1 1982.53   658.8 1983.99     686 1983.34     700 1985.95
   738.6 1980.31   764.11980.805   810.7 1979.02   819.51980.766   832.5 1984.25
   887.1 1983.43   920.8 1980.62   938.1 1983.74   986.1 1980.61  1001.7 1984.89
  1031.4 1984.55  1035.7 1986.24  1139.9 1989.63  1235.2 1995.63  1290.3 2009.04
#Mann= 9 ,-1 , 0
       0      .1       0     280     .04       0     410    .035       0
     620      .1       0   764.1    .045       0   819.5    .035       0
  943.32      .1       0 1023.32    .035       0 1153.32      .1       0
#XS Ineff= 2 , 0
             484 1987.53
Permanent Ineff=
       F       F
Bank Sta=764.1,819.5
XS Rating Curve= 0 ,0
Exp/Cntr=0.3,0.1

Type RM Length L Ch R = 1 ,3546    ,563.6,570.4,555.7
XS GIS Cut Line= 3
      2165179.54      198692.028     2165491.142      198254.104
     2166016.384      197627.849
#Sta/Elev= 30
       0 2027.02    29.6 2024.88    69.2 2018.86   137.1 2015.92   210.7 2008.95
   235.1 2002.39   239.1 2000.49   250.8 1991.11     256 1988.61   287.4  1988.2
   312.6 1985.77   394.3 1982.67   413.1 1983.52   468.6 1981.65   520.9 1981.99
   524.41979.817     529 1976.94   545.6 1976.69   573.41979.936   639.8 1980.98
   686.8 1979.12   735.8 1978.72   759.7 1980.83   809.4 1980.85   831.3 1982.22
     901 1981.13  1044.2 1981.11    1098 1983.28    1228  1993.7  1354.8 1996.14
#Mann= 5 ,-1 , 0
       0      .1       0     210     .04       0     330      .1       0
   524.4    .045       0   573.4      .1       0
#XS Ineff= 2 , 0
          381.42 1985.81 1089.37         1985.71
Permanent Ineff=
       F       F
Bank Sta=524.4,573.4
XS Rating Curve= 0 ,0
Exp/Cntr=0.3,0.1

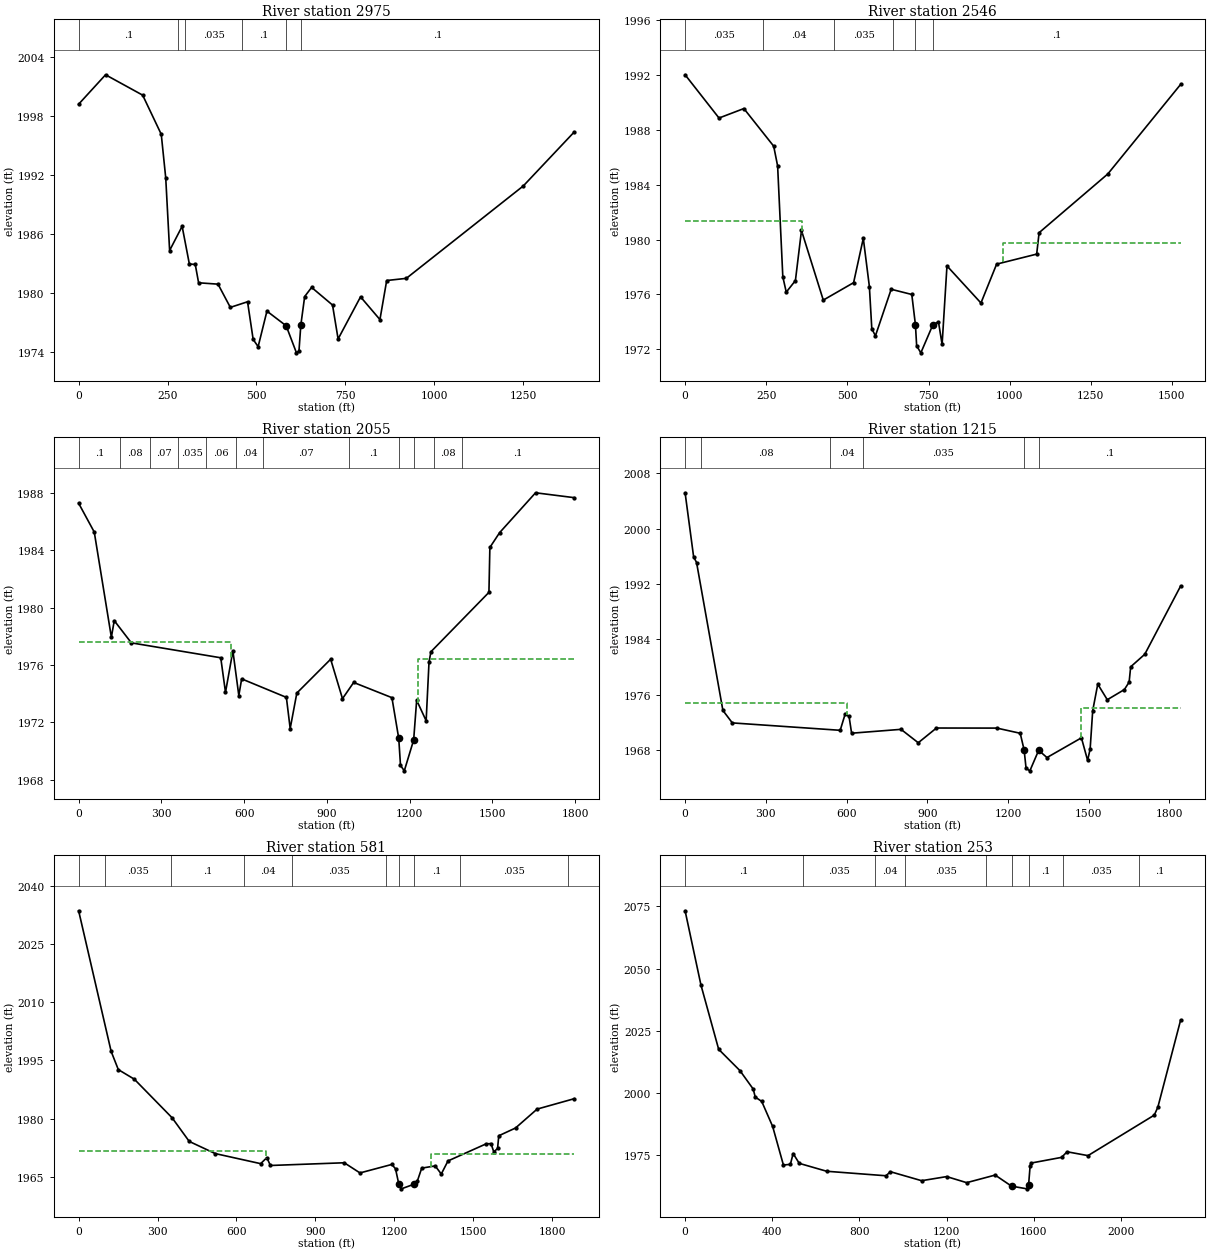
Type RM Length L Ch R = 1 ,2975    ,427.6,429.5,424.3
XS GIS Cut Line= 2
     2165584.037      198974.034     2166344.284      197806.512
#Sta/Elev= 30
       0 1999.21    75.7  2002.2     180 2000.13   232.3 1996.15   244.9 1991.71
   255.8 1984.34     291  1986.8   311.3 1982.97   327.9 1982.92   337.3 1981.06
   391.9 1980.92   426.5 1978.56   474.9 1979.13   490.7  1975.3   504.7 1974.57
   529.4 1978.18   583.51976.688   612.4 1973.94   619.5 1974.13  624.661976.753
   635.5 1979.66     655 1980.59   713.8  1978.8   729.5 1975.35   792.6 1979.63
   847.1 1977.32   866.1 1981.29   921.3 1981.51  1250.1  1990.9  1393.2 1996.38
#Mann= 6 ,-1 , 0
       0      .1       0     280     .04       0     300    .035       0
     460      .1       0   583.5    .045       0  624.66      .1       0
Bank Sta=583.5,624.66
XS Rating Curve= 0 ,0
Exp/Cntr=0.3,0.1

Type RM Length L Ch R = 1 ,2546    ,490.8,490.3,475.3
XS GIS Cut Line= 2
     2165918.864      199320.667     2166649.125      197979.759
#Sta/Elev= 30
       0    1992   104.5 1988.85   181.1 1989.54     273  1986.8   285.1 1985.36
   301.1 1977.29   311.7 1976.17   339.9 1977.01   358.6 1980.66   425.8 1975.59
   519.2 1976.86   549.1 1980.09   567.8 1976.58   575.3  1973.5   586.5 1972.99
     635 1976.38   698.5    1976  709.761973.783   713.5 1972.26   726.4 1971.75
   763.41973.789   780.7 1974.01   791.9 1972.36   806.9 1978.08   911.6 1975.38
   959.9 1978.21  1083.3 1978.94  1090.8  1980.5  1302.6 1984.78  1526.9  1991.3
#Mann= 6 ,-1 , 0
       0    .035       0     240     .04       0     460    .035       0
     640      .1       0  709.76    .045       0   763.4      .1       0
#XS Ineff= 2 , 0
          361.61 1981.32   980.8         1979.76
Permanent Ineff=
       F       F
Bank Sta=709.76,763.4
XS Rating Curve= 0 ,0
Exp/Cntr=0.3,0.1

Type RM Length L Ch R = 1 ,2055    ,834.3,840.9,850.5
XS GIS Cut Line= 2
     2166377.507       199850.39     2166929.215      198140.777
#Sta/Elev= 30
       0 1987.27    56.7 1985.26   118.7 1977.93   129.1 1979.09   191.1 1977.54
   515.2  1976.5   532.4 1974.09   559.2 1976.98   580.7 1973.87     591 1975.03
   753.1 1973.74   766.9 1971.57     791 1974.04   913.6  1976.4   956.5 1973.65
     997 1974.78  1135.7 1973.72  1160.51970.875  1166.8    1969  1180.6 1968.62
 1214.481970.769  1225.4 1973.54  1259.8 1972.11  1270.2  1976.2  1277.1 1976.92
  1487.4 1981.06  1490.8 1984.19  1526.1 1985.22  1656.4    1988  1796.4 1987.66
#Mann= 12 ,-1 , 0
       0      .1       0     150     .08       0     260     .07       0
     360    .035       0     460     .06       0     570     .04       0
     670     .07       0     980      .1       0  1160.5    .045       0
 1214.48      .1       0    1290     .08       0    1390      .1       0
#XS Ineff= 2 , 0
          553.15 1977.63 1230.13          1976.4
Permanent Ineff=
       F       F
Bank Sta=1160.5,1214.48
XS Rating Curve= 0 ,0
Exp/Cntr=0.3,0.1

Type RM Length L Ch R = 1 ,1215    ,630.8,633.6,639.3
XS GIS Cut Line= 2
     2166688.204      200147.645     2167736.815      198633.756
#Sta/Elev= 30
       0 2005.17    31.7 1995.91    42.6 1995.09   140.5  1973.7   175.5  1971.9
   576.4 1970.83   594.9 1973.19   609.4 1972.83   618.8 1970.41   802.4 1970.97
   866.5 1969.03   934.1 1971.16  1158.7 1971.15  1245.4  1970.4 1259.911967.997
  1267.2 1965.33  1281.3 1964.97    1314 1967.94  1344.8 1966.89  1472.9 1969.74
  1495.9 1966.48  1505.3 1968.13  1514.8 1973.67  1533.6  1977.5    1569 1975.25
  1632.5 1976.72  1650.2  1977.8  1655.9 1980.01  1708.3 1981.82  1841.6 1991.69
#Mann= 6 ,-1 , 0
       0      .1       0      60     .08       0     540     .04       0
     660    .035       0 1259.91    .045       0    1314      .1       0
#XS Ineff= 2 , 0
          600.62 1974.78 1471.62         1974.02
Permanent Ineff=
       F       F
Bank Sta=1259.91,1314
XS Rating Curve= 0 ,0
Exp/Cntr=0.3,0.1

Type RM Length L Ch R = 1 ,581     ,335.3,328,294
XS GIS Cut Line= 2
     2166945.148        200453.2     2168250.326      199094.201
#Sta/Elev= 30
       0 2033.56   123.6 1997.32   150.9 1992.62   211.8 1990.15   355.6 1980.19
   420.6 1974.11   519.4 1970.98   692.1 1968.38   715.6 1969.93   729.2 1967.91
    1010 1968.61  1069.8 1965.99  1190.9 1968.18  1204.9 1967.06  1217.61963.042
  1227.1 1961.89  1274.71963.068  1288.4    1964  1304.6 1967.23  1355.7  1967.8
  1378.9 1965.71  1404.4 1969.08  1549.2 1973.48  1568.1 1973.55  1578.5 1971.41
  1592.9 1972.29  1597.5 1975.57  1661.2 1977.57  1743.2 1982.44  1884.2 1985.12
#Mann= 10 ,-1 , 0
       0      .1       0     100    .035       0     350      .1       0
     630     .04       0     810    .035       0    1170      .1       0
  1217.6    .045       0  1274.7      .1       0    1450    .035       0
    1860      .1       0
#XS Ineff= 2 , 0
          712.07 1971.62 1339.53         1970.95
Permanent Ineff=
       F       F
Bank Sta=1217.6,1274.7
XS Rating Curve= 0 ,0
Exp/Cntr=0.3,0.1

Type RM Length L Ch R = 1 ,253     ,,,
XS GIS Cut Line= 4
2167191.04535981200918.2281095532167987.45576411199826.274781786
2168233.22303731199446.7354484882168500.76715751199060.974158906
#Sta/Elev= 30
       0  2073.2    72.8 2043.35     154 2017.56   251.5 2009.01   312.4  2001.6
   321.8 1998.38   351.5 1996.63   401.6 1986.59     451 1971.09   482.9 1971.35
   495.6 1975.69   523.8 1971.75   649.4 1968.58   921.5 1966.77   941.8  1968.4
    1085 1964.79    1200 1966.44  1291.6    1964  1422.3 1967.05  1497.4  1962.6
  1568.5 1961.52  1575.7 1963.09  1582.5  1970.5  1586.4 1971.86  1727.1 1974.16
  1752.2 1976.41  1848.2 1974.86  2152.3 1991.13  2168.7 1994.33  2273.2 2029.33
#Mann= 9 ,-1 , 0
       0      .1       0     540    .035       0     870     .04       0
    1010    .035       0 1381.53      .1       0  1497.4    .045       0
  1575.7      .1       0 1731.53    .035       0 2083.69      .1       0
Bank Sta=1497.4,1575.7
XS Rating Curve= 0 ,0
Exp/Cntr(USF)=0,0
Exp/Cntr=0.3,0.1
Stream Node=River 1         ,Reach 1         , 0 , 0 ,Upstream end
Stream Node=River 1         ,Reach 1         , 0 , 1 ,Downstream end
Stream Node=POTTSCK         ,Main            , 0 , 0 ,Upstream end
Stream Node=POTTSCK         ,Main            , 0 , 1 ,Downstream end
Stream Node=River (Missing) ,Reach (Missing) , 0 , 0 ,Upstream end
Stream Node=River (Missing) ,Reach (Missing) , 0 , 1 ,Downstream end
LCMann Table=0

Chan Stop Cuts=-1
Use User Specified Reach Order=0
Composite Channel Slope=5